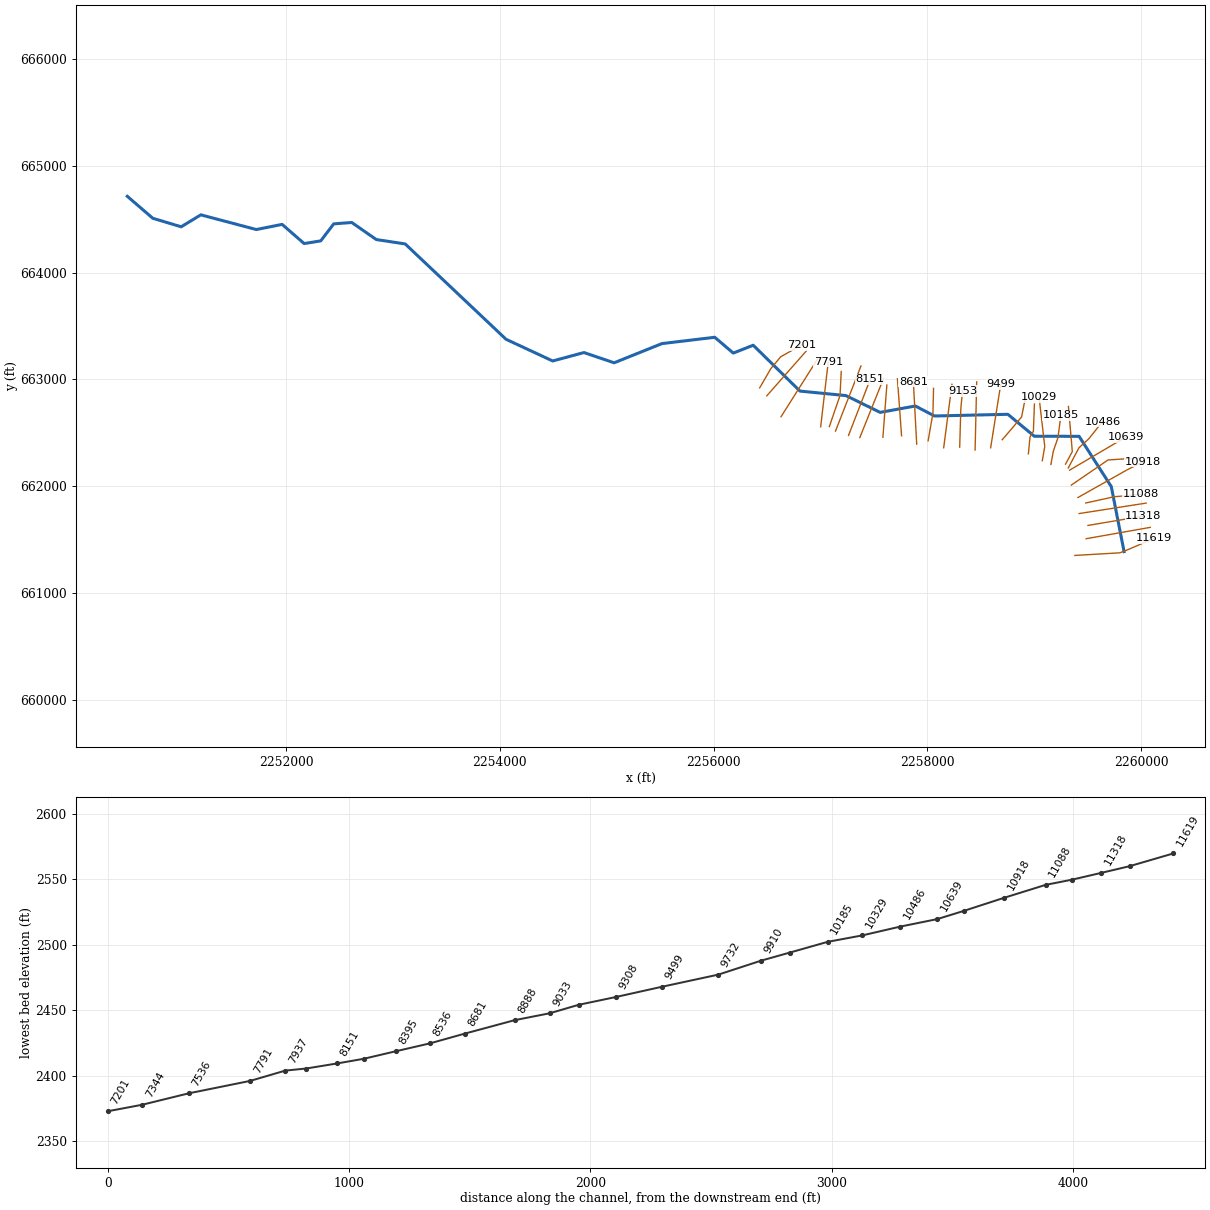
--- PNTHRNT1.prj (project) ---

Proj Title=PNTHRNT1
Current Plan=p01
Default Exp/Contr=0,0
English Units
Geom File=g01
Flow File=f01
Plan File=p01
BEGIN DESCRIPTION:
----------MODEL BY WOOD PLC 2022----------
AFH study
Randolph County, WV
HEC-RAS Version: RAS 6.2
Vertical Datum: NAVD88
Projection: NAD 1983 StatePlane West Virginia S FIPS 4702 (US Feet)
Terrain: 1-meter LIDAR (FEMA Region III 3DEP collected 2016-2018)
Land Use: 2019 NLCD
Hydrologic Method:
WV SIR2010-5033 regression equations
Additional Model Notes:
None
END DESCRIPTION:
DSS Export Rating Curves= 0
DSS Export Rating Curve Sorted= 0
DSS Export Volume Flow Curves= 0
DXF OffsetX= 0
DXF OffsetY= 0
DXF ScaleX= 0
DXF ScaleY= 0

--- PNTHRNT1.p01 (plan) ---

Plan Title=Floodplain
Program Version=6.20
Short Identifier=Floodplain
Geom File=g01
Flow File=f01
Subcritical Flow
K Sum by GR= 0
Std Step Tol= 0.01
Critical Tol= 0.01
Num of Std Step Trials= 20
Max Error Tol= 0.3
Flow Tol Ratio= 0.001
Split Flow NTrial= 30
Split Flow Tol= 0.02
Split Flow Ratio= 0.02
Log Output Level= 0
Friction Slope Method= 1
Unsteady Friction Slope Method= 2
Unsteady Bridges Friction Slope Method= 1
Parabolic Critical Depth
Global Vel Dist= 0 , 0 , 0
Global Log Level= 0
CheckData=True
Encroach Param=-1 ,0,0, 0
Mapping Interval=1HOUR
Computation Time Step Use Courant=        0
Computation Time Step Use Time Series=    0
Computation Time Step Count To Double=0
Computation Time Step Max Doubling=0
Computation Time Step Max Halving=0
Computation Time Step Residence Courant=0
Run HTab= 0
Run UNet= 0
Run Sediment= 0
Run PostProcess= 0
Run WQNet= 0
Run RASMapper=-1
UNET Theta= 0
UNET Theta Warmup= 0
UNET ZTol= 0
UNET ZSATol= 0
UNET MxIter= 0
UNET Max Iter WO Improvement= 0
UNET MaxInSteps= 0
UNET DtIC= 0
UNET DtMin= 0
UNET MaxCRTS= 0
UNET WFStab= 0
UNET SFStab= 0
UNET WFX= 1
UNET SFX= 1
UNET Gravity=32.174
UNET 1D Methodology=Finite Difference
UNET DSS MLevel= 1
UNET Pardiso=0
UNET DZMax Abort= 0
UNET Use Existing IB Tables= 0
UNET Froude Reduction=False
UNET Froude Limit= 0
UNET Froude Power= 0
UNET D1 Cores= 0
UNET WindReference=Eulerian
UNET WindDragFormulation=Hsu (1988)
UNET D2 Coriolis=0
UNET D2 Cores= 0
UNET D2 Theta= 1
UNET D2 Theta Warmup= 1
UNET D2 Z Tol= 0.01
UNET D2 Volume Tol= 0.01
UNET D2 Max Iterations= 20
UNET D2 Equation= 0
UNET D2 RampUpFraction=0.1
UNET D2 TimeSlices= 1
UNET D2 Turbulence Formulation=Non-Conservative (original)
UNET D2 Eddy Viscosity=0.3
UNET D2 Transverse Eddy Viscosity=0.1
UNET D2 Smagorinsky Mixing=0
UNET D2 BCVolumeCheck=0
UNET D2 Cores=0
UNET D2 SolverType=PARDISO (Direct)
UNET D2 Minimum Iterations= 2147483647
UNET D2 Maximum Iterations= 2147483647
UNET D2 Restart Number= 10
UNET D2 Relaxation Coeff=1.3
UNET D2 SOR Precondition Iterations= 10
UNET D2 ILUT Maximum Fill= 8
UNET D2 ILUT Tolerance=1E-08
UNET D1D2 MaxIter= 0
UNET D1D2 ZTol=0.01
UNET D1D2 QTol=0.1
UNET D1D2 MinQTol=1
Write IC File= 0
Write IC File at Fixed DateTime=0
Write IC File at Sim End=0
Echo Input=False
Echo Parameters=False
Echo Output=False
Write Detailed= 0
HDF Write Warmup=0
HDF Write Time Slices=0
HDF Flush=0
HDF Compression= 1
HDF Chunk Size= 1
HDF Spatial Parts= 1
HDF Use Max Rows=0
HDF Fixed Rows= 1
Calibration Method= 0
Calibration Iterations= 20
Calibration Max Change=0.05
Calibration Tolerance=0.2
Calibration Maximum=1.5
Calibration Minimum=0.5
Calibration Optimization Method= 1
WQ AD Non Conservative
WQ ULTIMATE=-1
WQ Max Comp Step=1HOUR
WQ Output Interval=15MIN
WQ Output Selected Increments= 0
WQ Output face flow=0
WQ Output face velocity=0
WQ Output face area=0
WQ Output face dispersion=0
WQ Output cell volume=0
WQ Output cell surface area=0
WQ Output cell continuity=0
WQ Output cumulative cell continuity=0
WQ Output face conc=0
WQ Output face dconc_dx=0
WQ Output face courant=0
WQ Output face peclet=0
WQ Output face adv mass=0
WQ Output face disp mass=0
WQ Output cell mass=0
WQ Output cell source sink temp=0
WQ Output nsm pathways=0
WQ Output nsm derived pathways=0
WQ Create Restart=0
WQ Fixed Restart=0
WQ System Summary=0
WQ Write To DSS=0
Sorting and Armoring Iterations= 10
XS Update Threshold= 0.02
Bed Roughness Predictor= 0
Hydraulics Update Threshold= 0.02
Energy Slope Method= 1
Volume Change Method= 1
Sediment Retention Method= 0
Sediment TS Multiplier= 1
Warm Up Method= 0
XS Weighting Method= 0
Number of US Weighted Cross Sections= 1
Number of DS Weighted Cross Sections= 1
Upstream XS Weight=0
Main XS Weight=1
Downstream XS Weight=0
Number of DS XS's Weighted with US Boundary= 1
Upstream Boundary Weight= 1
Weight of XSs Associated with US Boundary= 0
Number of US XS's Weighted with DS Boundary= 1
Downstream Boundary Weight= 0.5
Weight of XSs Associated with DS Boundary= 0.5
Percentile Method= 0
Sediment Output Level= 3
Mass or Volume Output= 0
Output Increment Type= 1
Profile and TS Output Increment= 1
Transport Output Increment 1
XS Output Flag= 0
XS Output Increment= 10
Read HDF5 Sediment Hotstart= 0
Sediment Hotstart Type= 0
Write Gradation File= 0
Read Gradation Hotstart= 0
Write HDF5 File= 1
Write Binary Output= 1
Write DSS Sediment File= 0
DSS Sediment Output Type= 1
SV Curve= 0
Specific Gage Flag= 0
Subcell Erosion Methods= 0
Subcell Deposition Methods= 0
Advection Scheme= 1
Matrix Solver= 0
Implicit Weighting Factor= 1
Maximum Outer Loop Convergence Iterations= 5
Convergence Maximum Absolute= 0.001
Convergence RMSE= 0.0001
Grain Fractions Max Abs Error= 0.001
Max Subgrid Regions= 1
Max Subgrid Length Scale= 3.402823E+38
Initial Layer Thickness= 3.402823E+38
Min Layer Thickness= 3.402823E+38
Max Layer Thickness= 3.402823E+38
Number of Layers= 5

--- PNTHRNT1.f01 (steady flow) ---

Flow Title=Flow
Program Version=6.20
Number of Profiles= 1
Profile Names=P100yr
River Rch & RM=PNTHRNT1,Main,11619
     547
River Rch & RM=PNTHRNT1,Main,7114
     831
River Rch & RM=PNTHRNT1,Main,5904
     925
River Rch & RM=PNTHRNT1,Main,4261
    1040
Boundary for River Rch & Prof#=PNTHRNT1,Main            , 1
Up Type= 0
Dn Type= 3
Dn Slope=0.02235
DSS Import GetInterval= 0
DSS Import GetPeak= 0
DSS Import FillOption= 0

--- PNTHRNT1.g01 (geometry) ---

Geom Title=Geometry
Program Version=6.20

River Reach=PNTHRNT1        ,Main
Reach XY= 30
      2259840.33      661387.483     2259720.538      661996.337
     2259419.205      662467.0982259000.90277996662467.799101815
     2258752.799      662673.1812258065.98271203662657.454708879
     2257887.413      662750.906     2257558.255      662690.982
2257237.63517093662848.510540684     2256807.719      662890.554
     2256370.452      663319.826     2256183.832      663246.505
 2256010.4225855663394.378023392     2255516.588      663335.356
2255069.19224757663155.450368453     2254786.712      663251.397
     2254494.241      663172.567     2254057.523      663375.637
      2253114.16 664268.25549709     2252843.698      664309.528
2252614.17084671664469.062559089     2252445.433      664456.319
     2252323.863      664296.973     2252168.593      664271.959
2251962.73524758664451.328376212     2251721.485      664403.063
     2251202.032      664540.7782251018.13743973 664428.84472768
2250752.63077361664508.657480413     2250513.572      664714.564

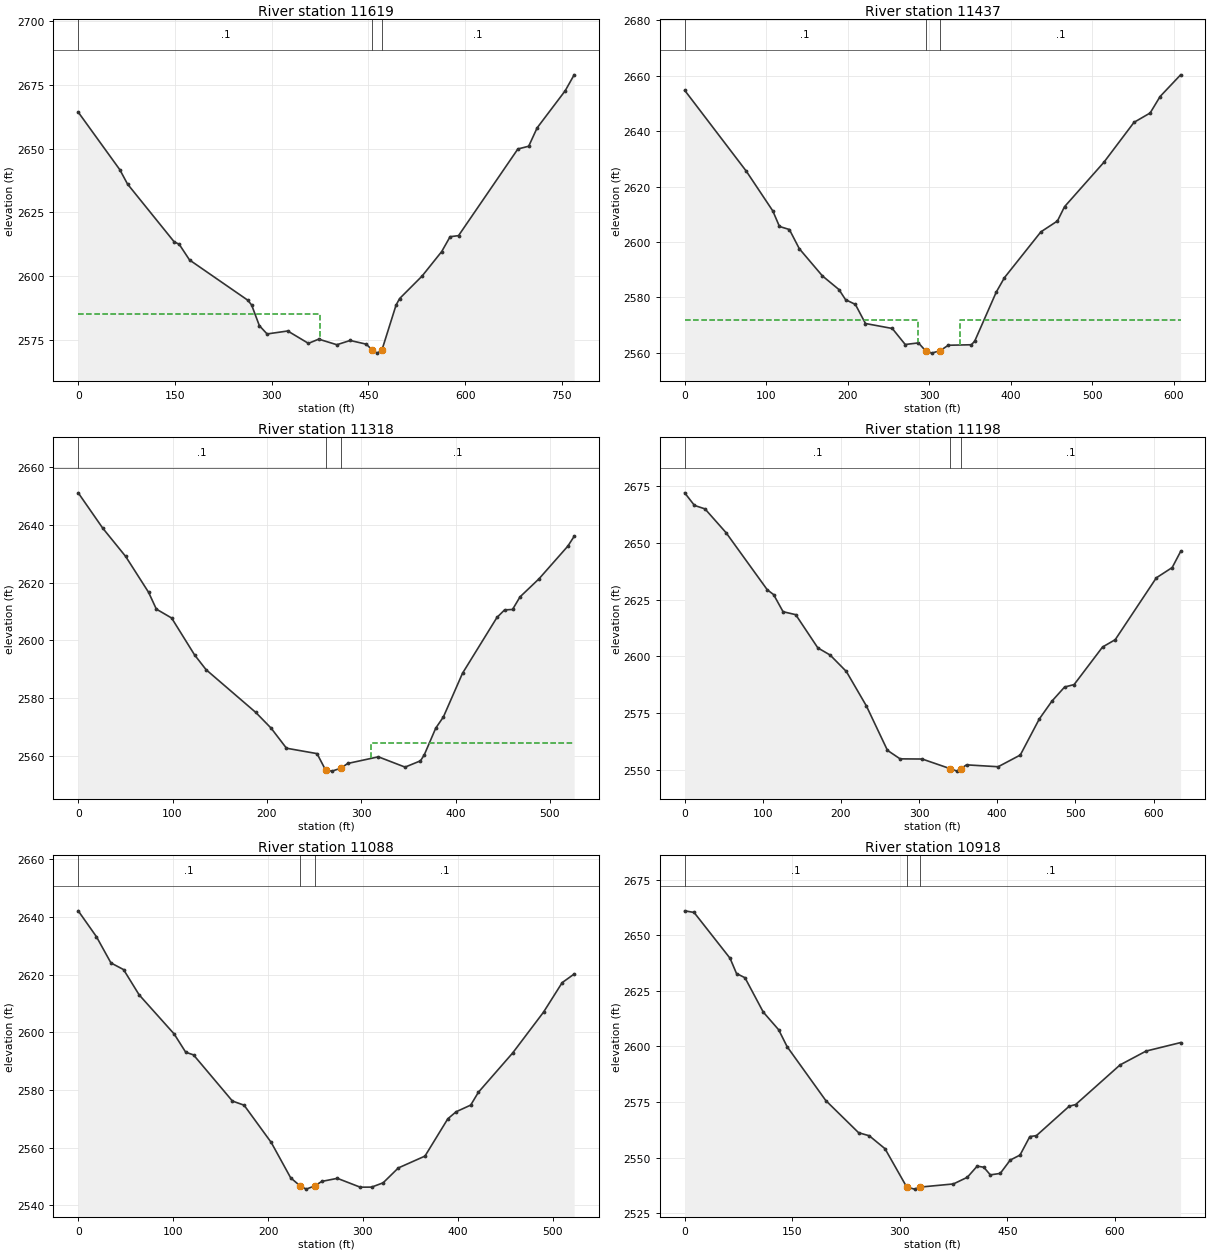
Type RM Length L Ch R = 1 ,11619   ,182.9,181.7,179.9
XS GIS Cut Line= 4
2259379.77681991661351.8280214632259799.76789089661376.266376854
2259845.98569201661393.0897348612260120.94876721661511.185779081
#Sta/Elev= 30
       0 2664.38    64.5 2641.76    76.5 2636.11   148.6 2613.48   156.7 2612.42
   172.7 2606.28   262.8 2590.51   268.9 2588.62   280.9 2580.49   292.9 2577.22
   324.9 2578.39     357 2573.53     373 2575.18   401.1 2572.99   421.7 2574.66
   446.8 2573.21   456.22570.822   463.7 2569.69   470.92570.829   492.9 2588.55
   498.4 2591.12   533.2 2599.95   563.7  2609.6   576.7 2615.43   589.8 2615.85
   681.8 2649.89   698.6 2650.98   711.7  2658.2   755.2 2672.77   769.1 2679.03
#Mann= 3, -1 ,  0
       0     0.1       0   456.2   0.045       0   470.9     0.1       0
#XS Ineff= 2 , 0
          374.98 2585.21
Permanent Ineff=
       F       F
Bank Sta=456.2,470.9
XS Rating Curve= 0 ,0
Exp/Cntr=0.3,0.1

Type RM Length L Ch R = 1 ,11437   ,119.1,119,118.8
XS GIS Cut Line= 2
2259485.66048094661508.3903544222260085.01431813 661614.58901767
#Sta/Elev= 30
       0  2654.7    75.7 2625.51   108.2 2611.19   116.3 2605.61   128.5  2604.5
   140.7 2597.58   169.1 2587.76   189.4 2582.84   197.5 2579.19   209.5  2577.5
   221.9 2570.61   254.8 2568.82   270.7 2563.04   286.9 2563.62   295.62560.812
   303.1 2559.93   313.62560.812   323.5 2562.77   351.9 2562.95     356 2564.27
   382.4 2581.93   392.5 2587.15   437.2 2603.66   457.5 2607.57   466.2 2612.72
   514.4  2628.7   551.5 2643.15   571.3 2646.52   583.5 2652.46   608.7 2660.28
#Mann= 3, -1 ,  0
       0     0.1       0   295.6   0.045       0   313.6     0.1       0
#XS Ineff= 2 , 0
          286.97 2572.05  337.48         2571.95
Permanent Ineff=
       F       F
Bank Sta=295.6,313.6
XS Rating Curve= 0 ,0
Exp/Cntr(USF)=0,0
Exp/Cntr=0.3,0.1

Type RM Length L Ch R = 1 ,11318   ,120.5,120.2,120
XS GIS Cut Line= 2
2259502.57471559 661632.669690792260020.81923563661720.291957906
#Sta/Elev= 30
       0 2651.07      26 2638.84    50.3 2629.05    74.6 2616.63    82.8 2610.83
      99 2607.75   123.3 2594.99   135.5 2589.87   188.2 2575.07   204.5 2569.61
   220.7 2562.69   253.1 2560.82   262.2 2555.12     269 2554.76   278.4 2555.79
   285.6 2557.41   318.1 2559.71   346.4 2556.15   362.7 2558.32   366.7 2560.35
   378.9 2569.63     387  2573.5   407.3 2588.64   443.8 2607.95   451.9 2610.56
   460.3  2610.7   468.2 2615.05   488.4 2621.33   518.9 2632.62   525.6 2636.01
#Mann= 3, -1 ,  0
       0     0.1       0   262.2   0.045       0   278.4     0.1       0
#XS Ineff= 2 , 0
                          310.01         2564.42
Permanent Ineff=
       F       F
Bank Sta=262.2,278.4
XS Rating Curve= 0 ,0
Exp/Cntr(USF)=0,0
Exp/Cntr=0.3,0.1

Type RM Length L Ch R = 1 ,11198   ,109.1,109.4,109.5
XS GIS Cut Line= 2
2259419.77592028661743.9049216262260046.83684456661841.822377459
#Sta/Elev= 30
       0 2671.93    12.5  2666.4      26 2664.87      53  2654.4   105.7 2629.32
   113.8 2627.21   125.9 2619.69   142.1 2618.38   170.4 2603.79   186.1 2600.65
   206.9 2593.42   232.6 2578.24   259.5 2558.76   275.7 2555.01     304 2554.94
   339.52550.736   348.6 2549.62   353.72550.752   360.7 2552.38   401.2 2551.55
   429.5 2556.69   453.8 2572.52     470 2580.39   486.2 2586.58   498.4 2587.66
   534.8 2604.17     551 2607.39   603.6 2634.57   623.9 2639.09   634.7 2646.16
#Mann= 3, -1 ,  0
       0     0.1       0   339.5   0.045       0   353.7     0.1       0
Bank Sta=339.5,353.7
XS Rating Curve= 0 ,0
Exp/Cntr(USF)=0,0
Exp/Cntr=0.3,0.1

Type RM Length L Ch R = 1 ,11088   ,167,170.7,172.4
XS GIS Cut Line= 4
2259481.42550507661842.8649896152259667.15475502661883.306035977
2259748.78575601 661901.279834362259996.67439204661923.747082338
#Sta/Elev= 30
       0  2642.1    19.2 2633.14    34.5 2624.04    47.8 2621.73    64.2 2612.98
   101.1 2599.42   113.3 2593.08   121.5 2592.17   162.5 2576.17   174.8 2574.73
   203.4 2561.81   223.9 2549.55   233.92546.745   240.3 2545.64   249.42546.789
   256.7 2548.32   273.1 2549.38   297.2 2546.31   309.2 2546.34   321.3 2547.83
   337.3 2552.98   365.4 2557.09   389.5 2570.03   398.2 2572.45   413.6 2574.77
   421.7 2579.22   457.8 2592.83   490.3 2606.97     510 2617.22   522.6 2620.19
#Mann= 3, -1 ,  0
       0     0.1       0   233.9   0.045       0   249.4     0.1       0
Bank Sta=233.9,249.4
XS Rating Curve= 0 ,0
Exp/Cntr(USF)=0,0
Exp/Cntr=0.3,0.1

Type RM Length L Ch R = 1 ,10918   ,167,169,168.9
XS GIS Cut Line= 3
2259408.71806562661894.0920956332259866.45551431662151.929865705
 2260014.5988506 662227.67627247
#Sta/Elev= 30
       0 2660.94    13.1 2660.21    63.3 2639.61    72.3 2632.76    84.1 2630.87
   109.6 2615.43   131.1 2607.47   142.8 2599.92   196.8 2575.67   242.6  2561.2
   257.4 2559.84   279.4 2554.02   309.82536.735   320.7 2535.85   328.12536.756
   374.8 2538.18   394.2 2541.17     408 2546.19   417.2 2545.68   426.3 2542.26
   440.1 2542.91   454.1 2548.92   467.7 2551.16   481.4 2559.47   490.6  2559.9
   536.3 2573.11   545.3 2573.87   607.2 2591.67   643.5  2597.9   691.7 2601.72
#Mann= 3, -1 ,  0
       0     0.1       0   309.8   0.045       0   328.1     0.1       0
Bank Sta=309.8,328.1
XS Rating Curve= 0 ,0
Exp/Cntr(USF)=0,0
Exp/Cntr=0.3,0.1

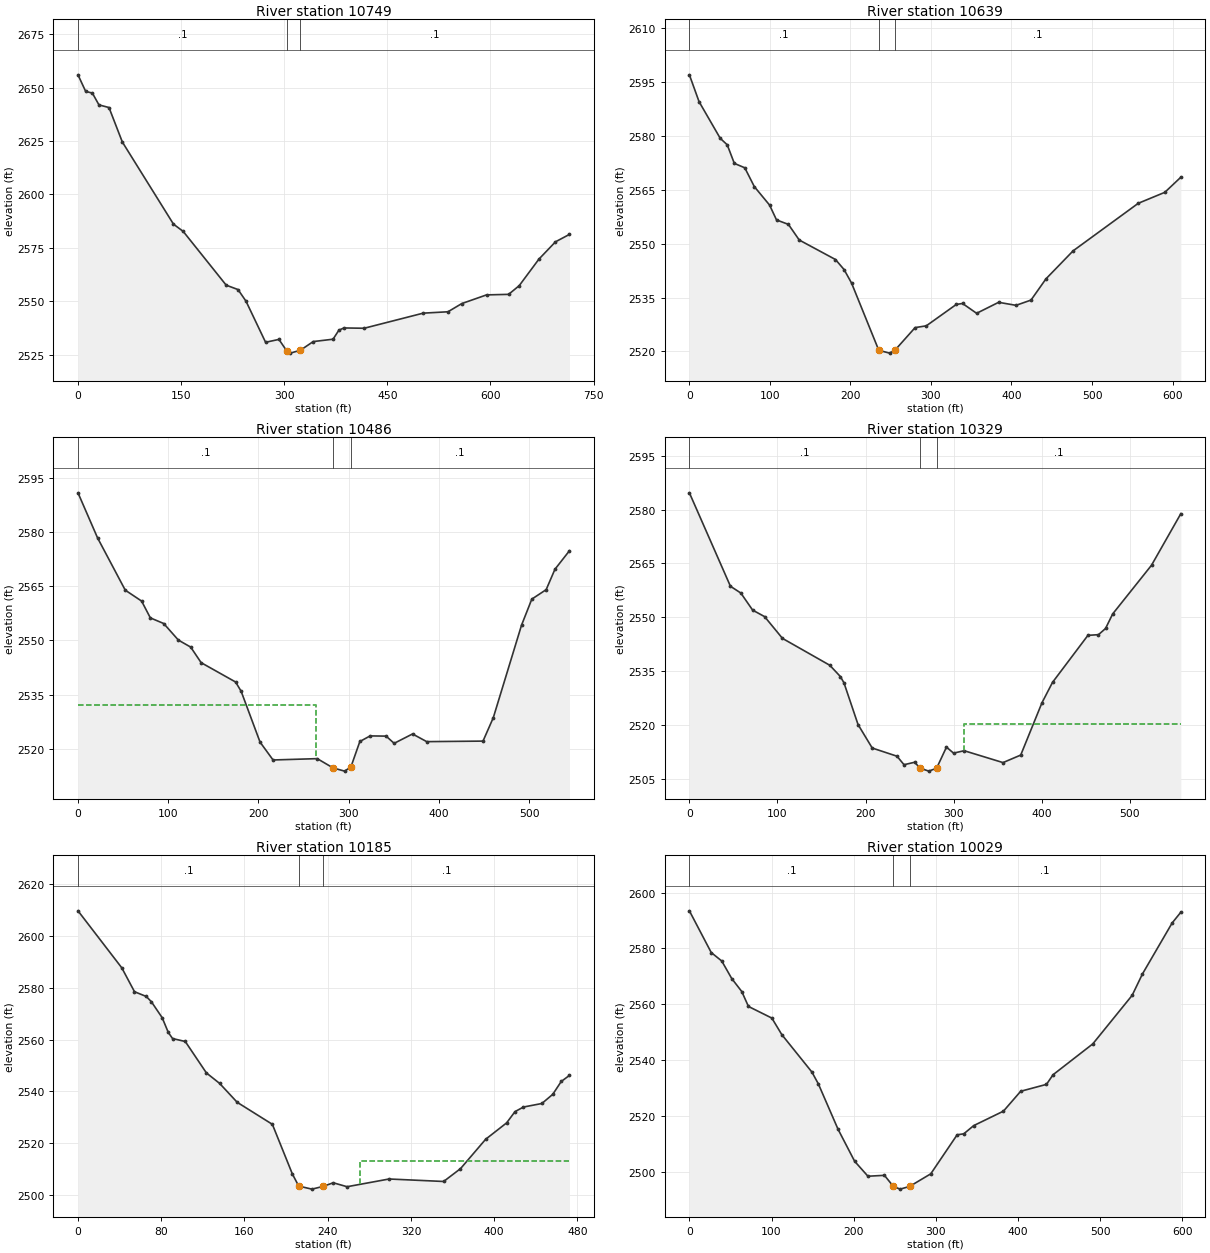
Type RM Length L Ch R = 1 ,10749   ,109.9,109.4,108.6
XS GIS Cut Line= 3
2259346.96422524662010.7278520532259690.54201529662245.867469163
2259988.46162726662265.272194847
#Sta/Elev= 30
       0 2655.96    11.2 2648.18    20.9 2647.43    30.5 2641.89    45.1 2640.66
    64.5 2624.53   138.9 2586.09   153.1 2582.67   215.6 2557.53   232.8 2555.47
   244.4 2550.04   272.9  2530.8   292.3 2532.15     3042526.613   308.9 2525.73
   323.62527.092   342.2 2531.14     371 2532.24   379.5 2536.46   386.8 2537.51
   416.3 2537.37   502.2 2544.44   538.2 2545.08   558.3 2548.92   594.3 2552.98
   626.4 2553.23   641.8 2557.29   670.5 2569.72   694.6 2577.82   714.9 2581.29
#Mann= 3, -1 ,  0
       0     0.1       0     304   0.045       0   323.6     0.1       0
Bank Sta=304,323.6
XS Rating Curve= 0 ,0
Exp/Cntr(USF)=0,0
Exp/Cntr=0.3,0.1

Type RM Length L Ch R = 1 ,10639   ,151.4,153.4,155.5
XS GIS Cut Line= 2
2259330.69251001662150.2440517812259856.51171404662460.058340869
#Sta/Elev= 30
       0 2597.01      12 2589.54    38.3 2579.33      47 2577.52    55.8 2572.35
    68.8 2571.12    80.6 2565.89    99.6 2560.73   108.2  2556.6     123 2555.36
   136.4 2551.01   181.4 2545.58   192.1 2542.78   201.4 2539.01   235.22520.296
   248.6 2519.51   255.22520.308   280.3 2526.62   294.2 2527.11   331.4 2533.06
   339.2 2533.34   356.7  2530.6     384 2533.66   405.6 2532.82   424.2 2534.28
   442.8 2540.19   476.5 2547.99   557.4 2561.23   590.4 2564.29   610.3  2568.5
#Mann= 3, -1 ,  0
       0     0.1       0   235.2   0.045       0   255.2     0.1       0
Bank Sta=235.2,255.2
XS Rating Curve= 0 ,0
Exp/Cntr(USF)=0,0
Exp/Cntr=0.3,0.1

Type RM Length L Ch R = 1 ,10486   ,148.1,156.6,165.3
XS GIS Cut Line= 4
2259318.00979458662170.8660402342259417.65876824662358.863588477
2259512.17119686662446.184854055 2259638.5302047662605.417750108
#Sta/Elev= 30
       0 2590.89    21.7  2578.4    52.4 2563.92    70.5  2560.9    80.2 2556.24
      95 2554.68   111.3 2550.08   124.9 2548.15   136.5 2543.83   174.7 2538.47
   180.8 2535.92   201.8 2521.82   216.2 2516.87   265.2 2517.24   282.82514.655
   295.5 2513.78   302.52514.938   312.4 2521.99   323.8 2523.54   341.5 2523.48
   350.4 2521.48   370.8 2524.08   386.5 2521.95   448.9  2522.1   460.3 2528.58
   491.6 2554.22     503 2561.44   518.9 2564.06   528.6  2569.7   544.7 2574.84
#Mann= 3, -1 ,  0
       0     0.1       0   282.8   0.045       0   302.5     0.1       0
#XS Ineff= 2 , 0
          263.94 2532.02
Permanent Ineff=
       F       F
Bank Sta=282.8,302.5
XS Rating Curve= 0 ,0
Exp/Cntr(USF)=0,0
Exp/Cntr=0.3,0.1

Type RM Length L Ch R = 1 ,10329   ,150,144.3,138.9
XS GIS Cut Line= 3
  2259292.208762662205.9778383922259356.00465132662324.323835974
2259319.64109328662746.300043792
#Sta/Elev= 30
       0 2584.69    46.6 2558.64    58.4 2556.75    71.8 2551.99    85.4 2550.17
   105.7  2544.1   159.4 2536.61   171.4 2533.47   175.5 2531.72   191.5 2520.07
   207.6 2513.53   235.7 2511.25   243.7 2508.88   255.7 2509.56   262.1  2507.9
   271.8 2507.09   280.72507.902   291.9 2513.79   299.9 2512.11     312 2512.78
   356.1 2509.47   376.2 2511.57   400.3 2526.14   412.3 2531.84   452.5 2544.95
   464.5 2545.14   472.5 2546.86   480.6 2550.92   524.7  2564.5     558 2578.88
#Mann= 3, -1 ,  0
       0     0.1       0   262.1   0.045       0   280.7     0.1       0
#XS Ineff= 2 , 0
                          312.04         2520.23
Permanent Ineff=
       F       F
Bank Sta=262.1,280.7
XS Rating Curve= 0 ,0
Exp/Cntr(USF)=0,0
Exp/Cntr=0.3,0.1

Type RM Length L Ch R = 1 ,10185   ,153.8,155.8,161
XS GIS Cut Line= 4
 2259155.6949715662203.7399284522259177.26846065662323.935082247
2259221.44274794662454.4033261092259249.18009112662665.001672502
#Sta/Elev= 30
       0 2609.81    42.1 2587.75    54.3 2578.52    65.6 2576.68    70.5 2574.66
    80.9 2568.47    86.8 2562.75    90.9 2560.39   103.1 2559.26   123.4  2547.1
   136.1 2543.05     153 2535.73   186.8 2527.21     206 2508.03   212.1 2503.32
   224.8 2502.14   235.8 2503.21   245.3  2504.6   258.6 2503.07     299 2506.06
   351.4  2505.1   367.6 2510.06   391.8 2521.44   411.9 2527.76     420 2532.13
   428.1  2533.9   445.8 2535.27   456.3 2538.83   464.4 2543.78   472.3 2546.14
#Mann= 3, -1 ,  0
       0     0.1       0   212.1   0.045       0   235.8     0.1       0
#XS Ineff= 2 , 0
                          270.83         2513.16
Permanent Ineff=
       F       F
Bank Sta=212.1,235.8
XS Rating Curve= 0 ,0
Exp/Cntr(USF)=0,0
Exp/Cntr=0.3,0.1

Type RM Length L Ch R = 1 ,10029   ,126.3,119.4,113.9
XS GIS Cut Line= 3
2259075.02619474662238.3702567372259098.15092048662371.104287686
2259044.96054878662831.691754331
#Sta/Elev= 30
       0 2593.46    26.6 2578.55    39.4 2575.53    51.6 2569.24    63.8 2564.61
    71.9 2559.29   100.4 2555.13   112.5 2549.23   149.2 2535.83     157 2531.63
   181.1 2515.34   201.2 2503.96   217.4 2498.61   237.5 2498.93   248.4 2494.96
   256.6    2494   268.12494.957   293.9 2499.47     326 2513.41   334.1 2513.77
   346.2  2516.7   382.4 2521.87   403.4 2528.97   434.8 2531.44   442.8 2534.88
   491.2 2545.91   539.1 2563.25   551.6 2570.87   587.8 2589.12   598.4 2592.97
#Mann= 3, -1 ,  0
       0     0.1       0   248.4   0.045       0   268.1     0.1       0
Bank Sta=248.4,268.1
XS Rating Curve= 0 ,0
Exp/Cntr(USF)=0,0
Exp/Cntr=0.3,0.1

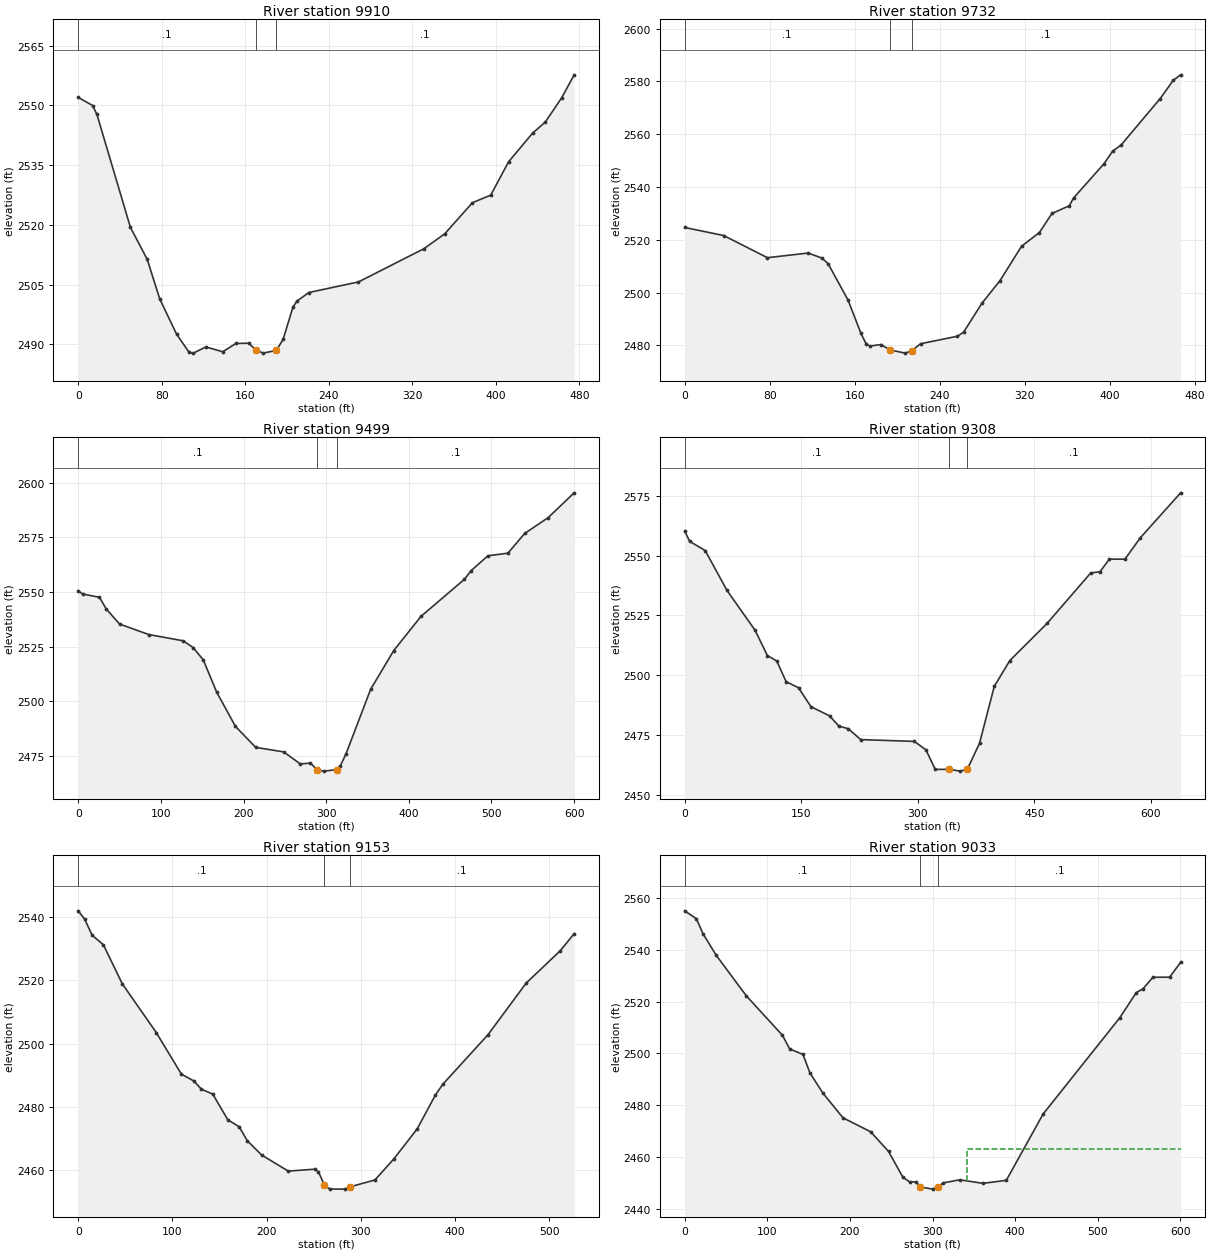
Type RM Length L Ch R = 1 ,9910    ,179.9,178,176.7
XS GIS Cut Line= 4
2258944.82950086662303.4131420692258960.26147103662460.801916835
2258991.83779645662515.0675878952259001.37032959662769.102318524
#Sta/Elev= 30
       0 2552.03    13.8 2549.99    17.9 2547.77      50  2519.4    66.1 2511.36
    78.1 2501.42    94.2  2492.6   106.3 2487.98   110.3 2487.81   122.3 2489.37
   138.4 2488.16   151.1 2490.23   163.2  2490.3   170.5 2488.58   177.1 2487.82
   189.8 2488.48   196.4 2491.34   205.7 2499.36   209.5 2500.86   220.9 2503.03
   268.5 2505.69   331.1 2514.02   351.1 2517.77   377.6 2525.57   395.2 2527.49
   412.3 2535.87   435.2 2543.03   447.4 2545.81   463.2 2551.96   475.1  2557.7
#Mann= 3, -1 ,  0
       0     0.1       0   170.5   0.045       0   189.8     0.1       0
Bank Sta=170.5,189.8
XS Rating Curve= 0 ,0
Exp/Cntr(USF)=0,0
Exp/Cntr=0.3,0.1

Type RM Length L Ch R = 1 ,9732    ,223.8,232.7,235.7
XS GIS Cut Line= 4
2258700.20357169662435.2107728742258771.25757911662517.470588201
 2258881.3470942662648.5295347432258917.54737573662832.026849159
#Sta/Elev= 30
       0  2524.7    36.7 2521.64    77.9 2513.25   116.3 2515.01   129.2  2513.1
     135 2510.99   153.7 2497.29   165.9 2484.64     171 2480.47   174.4  2479.8
   184.8 2480.36   193.12478.345   207.6 2477.11   213.72478.001   222.1 2480.67
   256.8  2483.5   262.5 2485.01   279.9 2496.03   296.8 2504.53   317.2 2517.61
   333.9 2522.76   345.8 2530.01   362.1 2532.92   366.1 2535.86   394.7 2548.79
   402.8 2553.52     411 2555.99   447.7 2573.52   459.9 2580.41   466.9  2582.5
#Mann= 3, -1 ,  0
       0     0.1       0   193.1   0.045       0   213.7     0.1       0
Bank Sta=193.1,213.7
XS Rating Curve= 0 ,0
Exp/Cntr(USF)=0,0
Exp/Cntr=0.3,0.1

Type RM Length L Ch R = 1 ,9499    ,187.8,191,191.2
XS GIS Cut Line= 2
2258591.84581113662359.7637999272258686.03440137662952.324775244
#Sta/Elev= 30
       0 2550.53     5.5 2549.05    25.7 2547.57    33.8 2542.27      50 2535.31
    85.4 2530.48     127 2527.62   139.1  2524.5   151.3 2518.88   167.5 2504.09
   190.2 2488.41   214.7 2478.77   248.5  2476.7   268.7 2471.18   280.9 2471.55
     289 2468.57   297.1 2467.88     3132468.569   317.3 2470.45     324  2475.8
   353.8 2505.39   381.7 2523.12   414.6 2538.78   467.2  2555.8   475.3 2559.76
   495.6 2566.59   519.9 2567.79   540.1 2576.82   568.5 2584.06     600 2595.45
#Mann= 3, -1 ,  0
       0     0.1       0     289   0.045       0     313     0.1       0
Bank Sta=289,313
XS Rating Curve= 0 ,0
Exp/Cntr(USF)=0,0
Exp/Cntr=0.3,0.1

Type RM Length L Ch R = 1 ,9308    ,155.6,155.4,154.7
XS GIS Cut Line= 2
2258446.43910581662338.7372756982258461.20957911662976.832535733
#Sta/Elev= 30
       0 2560.21     6.4 2555.92    26.4 2552.09    54.5 2535.43    90.5 2518.87
   106.5 2508.26   118.5 2506.01   130.5 2497.39   146.5 2494.83   162.5 2486.94
   186.5  2483.1   198.5 2478.83   210.5 2477.76   226.5 2473.21   295.6 2472.45
   310.5 2468.93   322.5 2460.76   340.12460.801   354.5 2460.05   363.82460.828
   379.5 2471.69   398.5 2495.44   418.5 2506.19   466.6 2521.75   522.6 2542.75
   534.6 2543.25   546.6 2548.52   566.6 2548.48   586.4 2557.39   638.3 2576.17
#Mann= 3, -1 ,  0
       0     0.1       0   340.1   0.045       0   363.8     0.1       0
Bank Sta=340.1,363.8
XS Rating Curve= 0 ,0
Exp/Cntr(USF)=0,0
Exp/Cntr=0.3,0.1

Type RM Length L Ch R = 1 ,9153    ,121.7,120,119.2
XS GIS Cut Line= 3
2258302.23147847 662366.419943882258312.67001941662723.070092727
2258328.32783082662891.826504621
#Sta/Elev= 30
       0 2541.88     6.8 2539.27    14.8 2534.19    26.8 2531.13    46.8 2518.83
    82.8 2503.48   109.5 2490.34   122.8 2488.17   130.8 2485.56   142.8 2484.05
   158.8 2475.92   170.8 2473.73   179.5 2469.29   194.6 2464.83   222.9 2459.74
   250.9 2460.34   254.9 2459.54   261.2 2455.37   266.9 2454.07   282.9 2454.05
   288.1 2454.74   314.9 2456.95   334.8 2463.53   359.7 2473.05     379 2483.72
     387 2487.17     435 2502.83   475.4 2519.08   511.6  2529.3   526.3 2534.68
#Mann= 3, -1 ,  0
       0     0.1       0   261.2   0.045       0   288.1     0.1       0
Bank Sta=261.2,288.1
XS Rating Curve= 0 ,0
Exp/Cntr(USF)=0,0
Exp/Cntr=0.3,0.1

Type RM Length L Ch R = 1 ,9033    ,144.6,145,143.3
XS GIS Cut Line= 2
2258152.27761864662359.1637643012258229.86631745662954.455952035
#Sta/Elev= 30
       0 2555.06    14.1 2552.04    22.2  2546.2    38.3 2537.82    74.6 2522.24
   118.4 2506.98   127.1  2501.7   143.2 2499.62   151.6 2492.47   167.4 2484.63
   191.6 2475.13   225.1 2469.74   246.8 2462.14   264.2 2452.13   272.3 2450.42
   280.1 2450.39   285.42448.411   300.5 2447.59     3072448.409   312.6 2449.98
   332.8 2451.19     361 2449.83   389.3 2450.98   433.8 2476.56   526.6 2513.75
   546.6 2523.46   554.9    2525   566.8  2529.4     587 2529.44   600.3 2535.19
#Mann= 3, -1 ,  0
       0     0.1       0   285.4   0.045       0     307     0.1       0
#XS Ineff= 2 , 0
                          341.49         2463.07
Permanent Ineff=
       F       F
Bank Sta=285.4,307
XS Rating Curve= 0 ,0
Exp/Cntr(USF)=0,0
Exp/Cntr=0.3,0.1

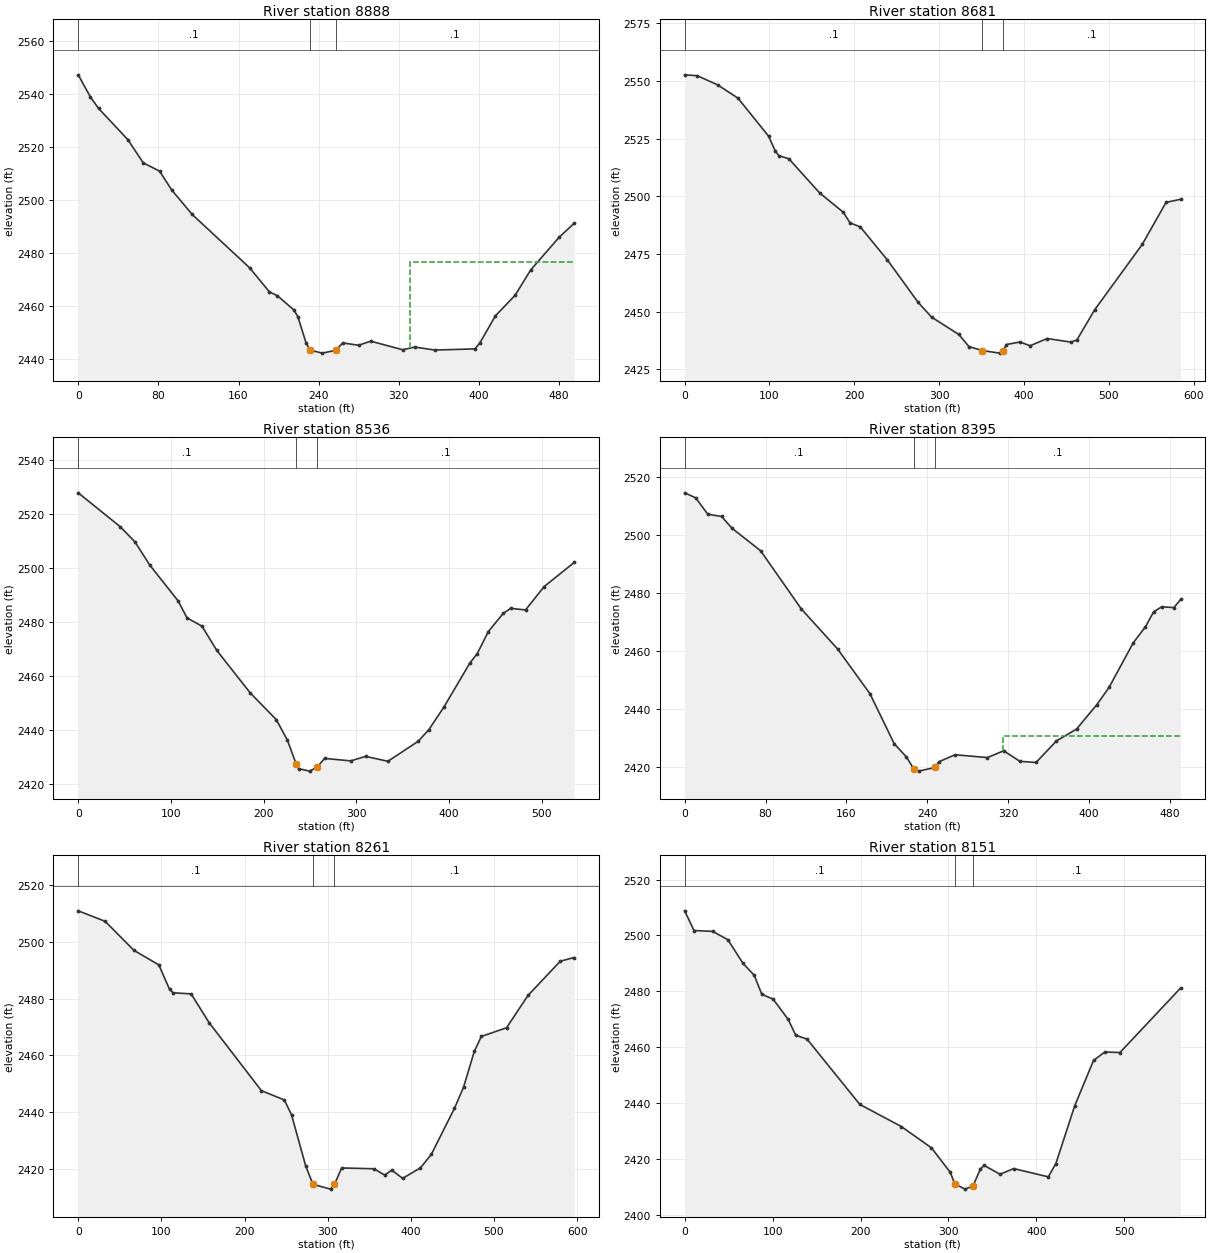
Type RM Length L Ch R = 1 ,8888    ,205.5,206.9,208.5
XS GIS Cut Line= 3
2258006.70266296662425.2119608272258052.00699015662684.093830539
2258057.55445879662916.162935174
#Sta/Elev= 30
       0 2547.29    12.1 2538.99    20.3 2534.63    49.6 2522.82    64.9  2514.1
    81.2 2510.97    93.4 2503.83   113.7 2494.66     171 2474.55   190.8 2465.44
   198.9 2463.98   215.2 2458.64   219.2 2456.13   227.4 2446.22   231.4 2443.47
   243.6 2442.34  257.07  2443.4     264 2446.19   279.9 2445.31   291.9 2446.85
   323.9 2443.61   335.9 2444.63   355.9  2443.5   395.9 2443.94   400.8 2446.13
   416.4  2456.4     436 2464.12   451.6 2473.69     480 2486.03     495  2491.3
#Mann= 3, -1 ,  0
       0     0.1       0   231.4   0.045       0  257.07     0.1       0
#XS Ineff= 2 , 0
                          331.26         2476.63
Permanent Ineff=
       F       F
Bank Sta=231.4,257.07
XS Rating Curve= 0 ,0
Exp/Cntr(USF)=0,0
Exp/Cntr=0.3,0.1

Type RM Length L Ch R = 1 ,8681    ,145.1,144.5,145.9
XS GIS Cut Line= 2
2257899.88889829662394.4480647542257868.66315171662978.328793295
#Sta/Elev= 30
       0 2552.64    14.8 2552.26    38.8  2548.3    62.8 2542.54    98.9 2526.08
   106.9 2519.58   110.9 2517.67   122.9 2516.24     159 2501.51     187  2493.1
     195 2488.49     207 2486.77   239.1 2472.38   275.1 2454.13   291.1 2447.66
   323.2 2440.14   335.2 2434.89   350.92433.185   371.2 2432.06   375.3 2433.03
   379.3 2435.79   395.3 2436.88   407.3 2435.25   427.3 2438.39   455.4 2436.84
   462.4 2437.78   483.4 2450.85   539.5 2479.19   567.5 2497.36   584.7 2498.73
#Mann= 3, -1 ,  0
       0     0.1       0   350.9   0.045       0   375.3     0.1       0
Bank Sta=350.9,375.3
XS Rating Curve= 0 ,0
Exp/Cntr(USF)=0,0
Exp/Cntr=0.3,0.1

Type RM Length L Ch R = 1 ,8536    ,142.2,141.3,139.2
XS GIS Cut Line= 2
2257758.36129408662472.1398901572257719.47906371663005.374810758
#Sta/Elev= 30
       0 2527.98    45.2 2515.43    61.2 2509.75    77.2 2501.12   107.7 2487.85
   117.3 2481.53   133.4 2478.46   149.4 2469.45   185.5 2453.64   213.6 2443.72
   225.6 2436.05   234.8 2427.43   237.7  2425.5   249.7  2424.6   257.7 2426.13
   265.7 2429.34   293.8  2428.4   309.9 2430.08   333.9 2428.26   366.5 2435.67
     378 2439.99   394.1 2448.29   422.2 2464.71   430.2 2468.24   442.2 2476.46
   458.3 2483.22   466.3 2485.05   482.3 2484.48   502.4 2493.17   534.7  2502.1
#Mann= 3, -1 ,  0
       0     0.1       0   234.8   0.045       0   257.7     0.1       0
Bank Sta=234.8,257.7
XS Rating Curve= 0 ,0
Exp/Cntr(USF)=0,0
Exp/Cntr=0.3,0.1

Type RM Length L Ch R = 1 ,8395    ,135.9,133.6,128.8
XS GIS Cut Line= 2
2257583.87330377662458.3279378452257620.65350278662947.885069477
#Sta/Elev= 30
       0 2514.53    10.9 2512.81    22.9 2507.14    36.5 2506.39      47 2502.27
    75.1 2494.59   115.5 2474.48   151.3 2460.74   183.4 2445.28   207.4 2428.05
   219.5 2423.49   226.8 2419.33   231.5  2418.6   248.12419.885   251.6 2421.81
   267.6 2424.25   299.7 2423.27   315.7 2425.61   331.8 2421.98   347.8 2421.58
   367.9 2428.99   387.9  2433.1     408 2441.52     420 2447.43   444.1 2462.88
   456.1 2468.36   464.2 2473.53   472.2 2475.25   484.2 2474.97   490.9 2477.76
#Mann= 3, -1 ,  0
       0     0.1       0   226.8   0.045       0   248.1     0.1       0
#XS Ineff= 2 , 0
                          314.75          2430.8
Permanent Ineff=
       F       F
Bank Sta=226.8,248.1
XS Rating Curve= 0 ,0
Exp/Cntr(USF)=0,0
Exp/Cntr=0.3,0.1

Type RM Length L Ch R = 1 ,8261    ,109.7,110.3,109.9
XS GIS Cut Line= 2
2257367.69149134662455.141303918 2257589.7598554663008.611656511
#Sta/Elev= 30
       0    2511    32.4  2507.3    66.8  2497.1      97 2491.91   109.9 2483.25
   114.3 2482.07   135.8  2481.7   157.4 2471.55   220.3 2447.55   247.9 2444.27
   256.5 2439.05   273.7 2420.87   282.3 2414.51   303.4 2412.81   308.2 2414.48
   316.8 2420.28   355.6 2419.99   368.5 2417.78   377.2 2419.52   390.1  2416.6
   411.6 2420.32   424.6 2425.06   452.5 2441.34   463.4 2448.79   476.3 2461.38
   484.8 2466.68   515.1 2469.74   540.9 2481.15   579.7 2493.22   596.4 2494.53
#Mann= 3, -1 ,  0
       0     0.1       0   282.3   0.045       0   308.2     0.1       0
Bank Sta=282.3,308.2
XS Rating Curve= 0 ,0
Exp/Cntr(USF)=0,0
Exp/Cntr=0.3,0.1

Type RM Length L Ch R = 1 ,8151    ,128.1,127.9,128.1
XS GIS Cut Line= 2
2257262.10997659662475.3229263522257465.28886904663001.533428721
#Sta/Elev= 30
       0  2508.8    10.6 2501.76      32 2501.44    49.2 2498.45    66.3 2490.02
    79.2 2485.72    87.7 2478.96   100.6 2477.22   117.8 2469.94   126.3  2464.3
   139.2 2462.91   199.2 2439.56   246.4 2431.66   280.7 2424.03   302.1 2415.26
     307 2411.27   318.6 2409.26   327.9 2410.35   327.9 2410.38   336.4 2416.48
   340.7 2417.72   358.8 2414.57   374.2 2416.61   413.6 2413.65   422.2 2418.39
   443.6 2439.03   465.1 2455.32   477.9  2458.3   495.1 2458.12   564.1 2481.19
#Mann= 3, -1 ,  0
       0     0.1       0     307   0.045       0   327.9     0.1       0
Bank Sta=307,327.9
XS Rating Curve= 0 ,0
Exp/Cntr(USF)=0,0
Exp/Cntr=0.3,0.1

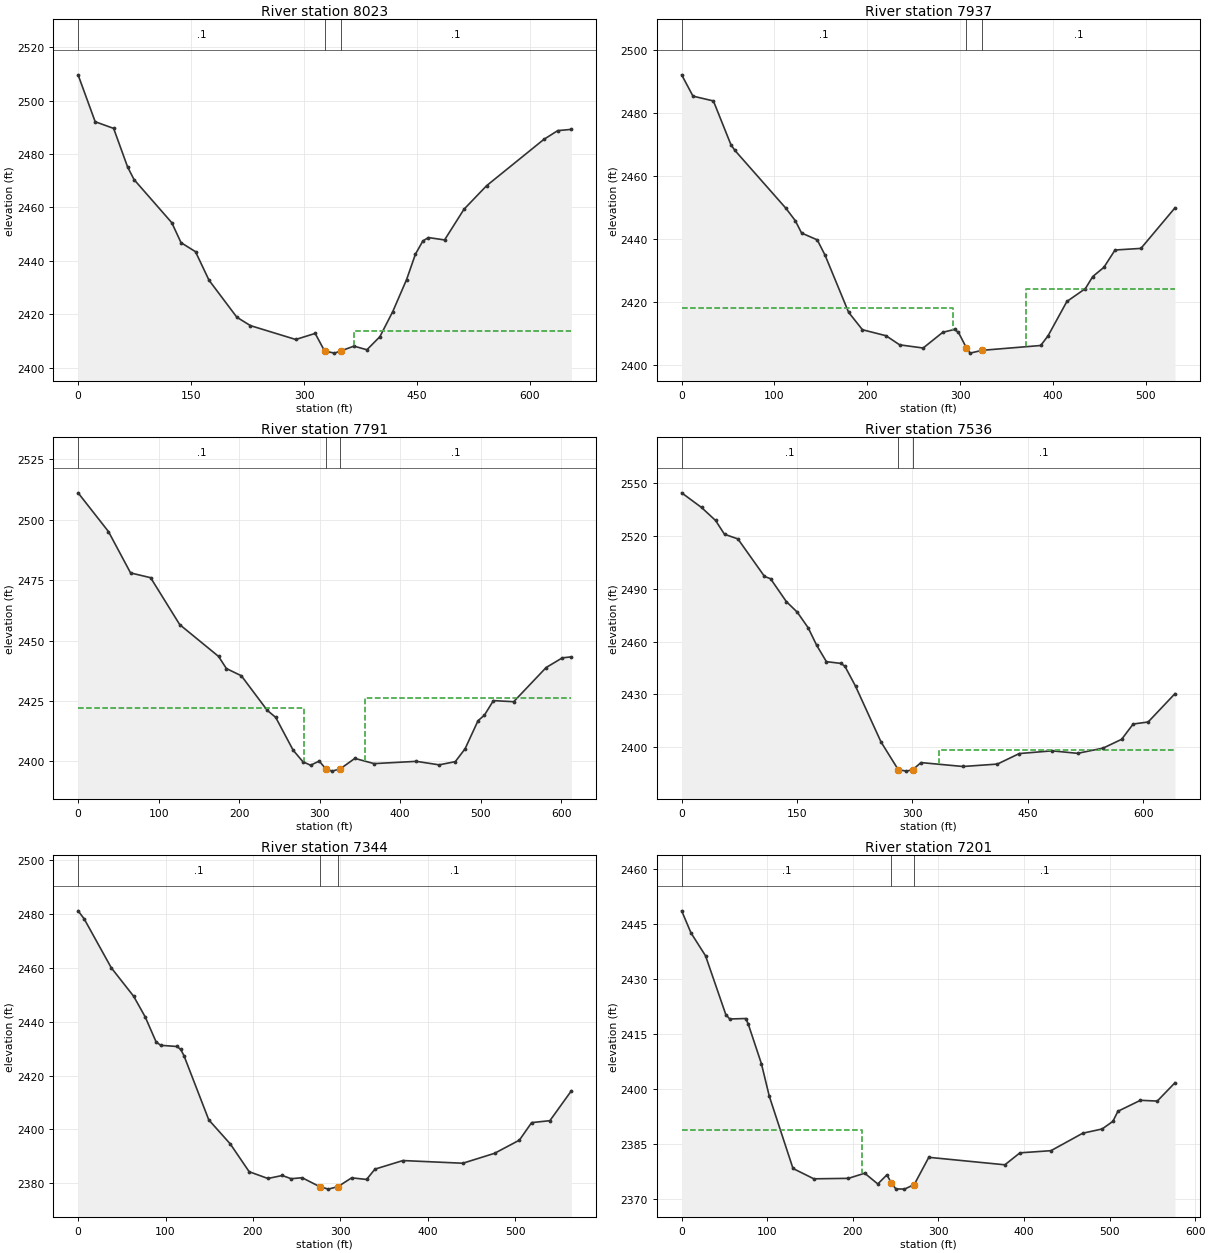
Type RM Length L Ch R = 1 ,8023    ,83.6,86.4,89.1
XS GIS Cut Line= 2
2257140.24116109662516.0154264072257378.74222047663126.093748739
#Sta/Elev= 30
       0 2509.68    22.7 2492.11    47.2 2489.61    65.7 2475.19    74.3 2470.44
   124.4 2454.28   136.7  2446.8   155.9 2443.42   173.8 2432.75   210.8 2418.86
   228.9 2415.71     289 2410.52   314.8  2412.8   327.32406.213   340.4 2405.41
   348.72406.226   366.3 2408.03   383.5 2406.67   400.7 2411.57   417.7 2420.92
   436.2 2432.99   447.9 2442.49   457.8 2447.44   465.1 2448.71   486.6 2447.82
   512.3 2459.29   542.4 2468.14   618.4 2485.49   636.9 2488.78     655 2489.24
#Mann= 3, -1 ,  0
       0     0.1       0   327.3   0.045       0   348.7     0.1       0
#XS Ineff= 2 , 0
                          365.97          2413.8
Permanent Ineff=
       F       F
Bank Sta=327.3,348.7
XS Rating Curve= 0 ,0
Exp/Cntr(USF)=0,0
Exp/Cntr=0.3,0.1

Type RM Length L Ch R = 1 ,7937    ,145.9,145.5,144.9
XS GIS Cut Line= 3
2257082.90162762662558.9915376832257182.55060128662849.719986606
2257193.85100036663073.673350087
#Sta/Elev= 30
       0 2492.06    12.2  2485.3    34.2 2483.78    53.1 2469.89    57.3 2468.12
   112.3 2449.75   122.4 2445.83   129.2  2441.9   146.1 2439.72   154.5 2434.88
   179.9 2416.75   194.8 2411.23   220.2 2409.33   234.9 2406.44   260.2 2405.43
   281.4 2410.42   294.1 2411.32   298.3 2410.36   306.8 2405.51   310.8 2403.81
   323.82404.701   386.9 2406.23   394.9 2409.34   415.1 2420.19     435 2424.26
     443  2428.1     455 2431.02     467 2436.51   494.9 2437.02   531.6 2449.89
#Mann= 3, -1 ,  0
       0     0.1       0   306.8   0.045       0   323.8     0.1       0
#XS Ineff= 2 , 0
          292.71 2418.09  370.72         2423.99
Permanent Ineff=
       F       F
Bank Sta=306.8,323.8
XS Rating Curve= 0 ,0
Exp/Cntr(USF)=0,0
Exp/Cntr=0.3,0.1

Type RM Length L Ch R = 1 ,7791    ,261.3,255.2,252.9
XS GIS Cut Line= 2
2257001.34730482662555.7325456452257072.38587976663164.451097766
#Sta/Elev= 30
       0 2511.19    37.7 2495.17    65.2 2478.03    90.1 2476.05   126.3 2456.61
   174.6 2443.43   184.2 2438.44   202.8 2435.45     235 2421.13   245.5 2418.21
   267.2  2404.6   279.3 2399.85   288.8  2398.4   299.5 2400.12   307.82396.896
   315.6 2395.96   325.72396.916   343.8 2401.23   367.7 2399.07   420.3 2400.01
   448.5 2398.56   468.6 2399.89   480.7 2405.21   496.8 2416.83   504.8 2419.15
   515.9 2425.16   541.1  2424.7   581.4 2438.85   601.5 2442.86   612.8 2443.28
#Mann= 3, -1 ,  0
       0     0.1       0   307.8   0.045       0   325.7     0.1       0
#XS Ineff= 2 , 0
          280.16 2422.21  356.13         2426.08
Permanent Ineff=
       F       F
Bank Sta=307.8,325.7
XS Rating Curve= 0 ,0
Exp/Cntr(USF)=0,0
Exp/Cntr=0.3,0.1

Type RM Length L Ch R = 1 ,7536    ,196.5,192.4,194.4
XS GIS Cut Line= 2
2256630.36983103662650.1290344412256973.23312529663192.261718211
#Sta/Elev= 30
       0 2544.56    25.8 2536.24    44.1 2528.84    55.7    2521    73.1 2518.39
   107.7 2497.08   115.6 2495.74   136.1 2482.76   150.3 2476.77   164.5 2467.89
   175.5 2457.98   188.2 2448.65   207.1 2447.64   212.3    2446   226.1 2434.69
   259.2 2403.04   281.62387.279   292.3 2386.44   300.62387.277   311.2  2391.3
   365.9 2389.07   410.6 2390.45     439 2396.42   481.6 2397.97   514.8 2396.55
   547.9 2399.49   572.1 2404.51   587.1  2413.2   606.6 2414.36   641.5 2430.46
#Mann= 3, -1 ,  0
       0     0.1       0   281.6   0.045       0   300.6     0.1       0
#XS Ineff= 2 , 0
                          334.77         2398.32
Permanent Ineff=
       F       F
Bank Sta=281.6,300.6
XS Rating Curve= 0 ,0
Exp/Cntr(USF)=0,0
Exp/Cntr=0.3,0.1

Type RM Length L Ch R = 1 ,7344    ,143.3,142.4,143.2
XS GIS Cut Line= 2
2256497.40302477662846.2545603272256870.27814575663269.860990285
#Sta/Elev= 30
       0 2481.25     6.9  2478.3      38 2460.05    63.6 2449.46    76.8 2441.78
    89.2 2432.53    94.5 2431.23   113.2 2430.79   117.4 2429.68   121.1  2427.4
   149.5  2403.5   174.1 2394.55   195.7 2384.22   217.1  2381.7   233.6 2382.81
   243.7 2381.61   256.3 2381.98   276.2 2378.69   286.3 2377.74   297.42378.698
   312.9 2381.94     330 2381.34   339.6 2385.18   371.6 2388.37   440.1 2387.37
   476.4 2391.06   504.8 2395.96   518.8 2402.48   539.7  2403.2   564.3 2414.33
#Mann= 3, -1 ,  0
       0     0.1       0   276.2   0.045       0   297.4     0.1       0
Bank Sta=276.2,297.4
XS Rating Curve= 0 ,0
Exp/Cntr(USF)=0,0
Exp/Cntr=0.3,0.1

Type RM Length L Ch R = 1 ,7201    ,90.6,87.5,86.2
XS GIS Cut Line= 4
2256430.70555622662920.5761240142256535.49107491 663101.38250921
2256626.92157652663211.3045729362256822.11028781 663322.25394567
#Sta/Elev= 30
       0 2448.63    10.9 2442.61    27.9 2436.37    51.6 2420.34    56.2 2419.15
    74.7 2419.28    77.6 2417.91    93.2 2406.96   102.4  2398.1   130.1 2378.41
   154.5 2375.59   194.9 2375.72   213.9 2377.12   229.2 2374.19   239.9 2376.68
   245.1 2374.41   250.3 2372.85   260.4 2372.78   271.8 2374.04   288.8 2381.45
   377.7 2379.41   395.3 2382.67   431.6 2383.26   468.7 2388.02   491.4 2389.18
   503.9 2391.25   509.8    2394   536.1 2396.99   555.8 2396.78   576.5 2401.78
#Mann= 3, -1 ,  0
       0     0.1       0   245.1   0.045       0   271.8     0.1       0
#XS Ineff= 2 , 0
          210.63 2388.89
Permanent Ineff=
       F       F
Bank Sta=245.1,271.8
XS Rating Curve= 0 ,0
Exp/Cntr(USF)=0,0
Exp/Cntr=0.3,0.1