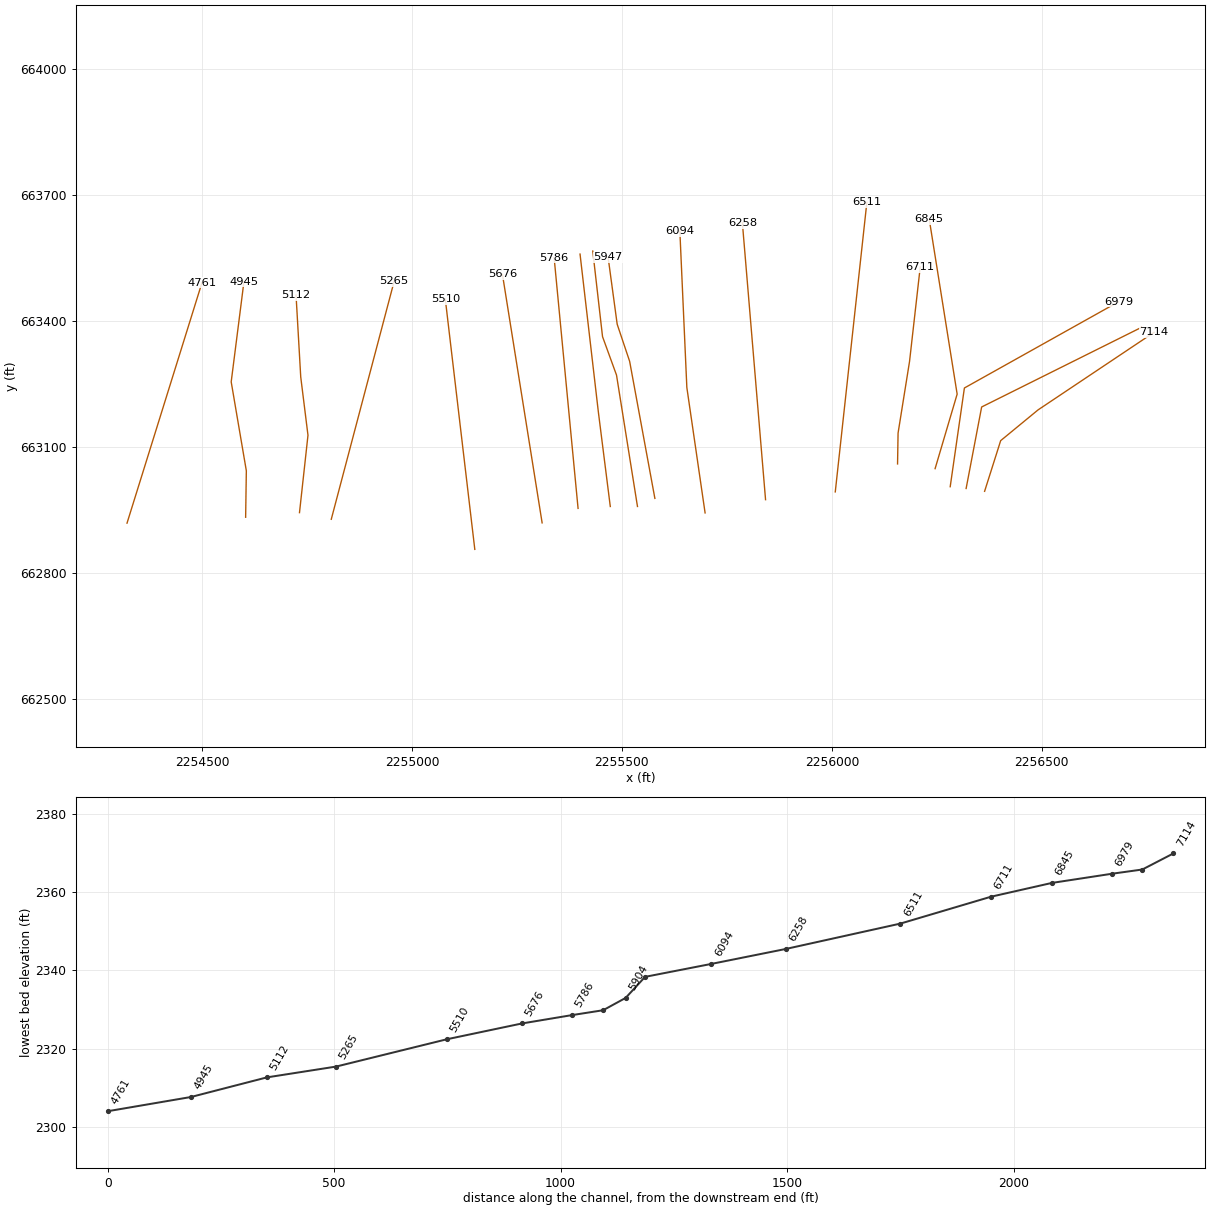
HEC-RAS study PNTHRNT1.prj: PNTHRNT1

--- PNTHRNT1.g01 (geometry) --- (continued)

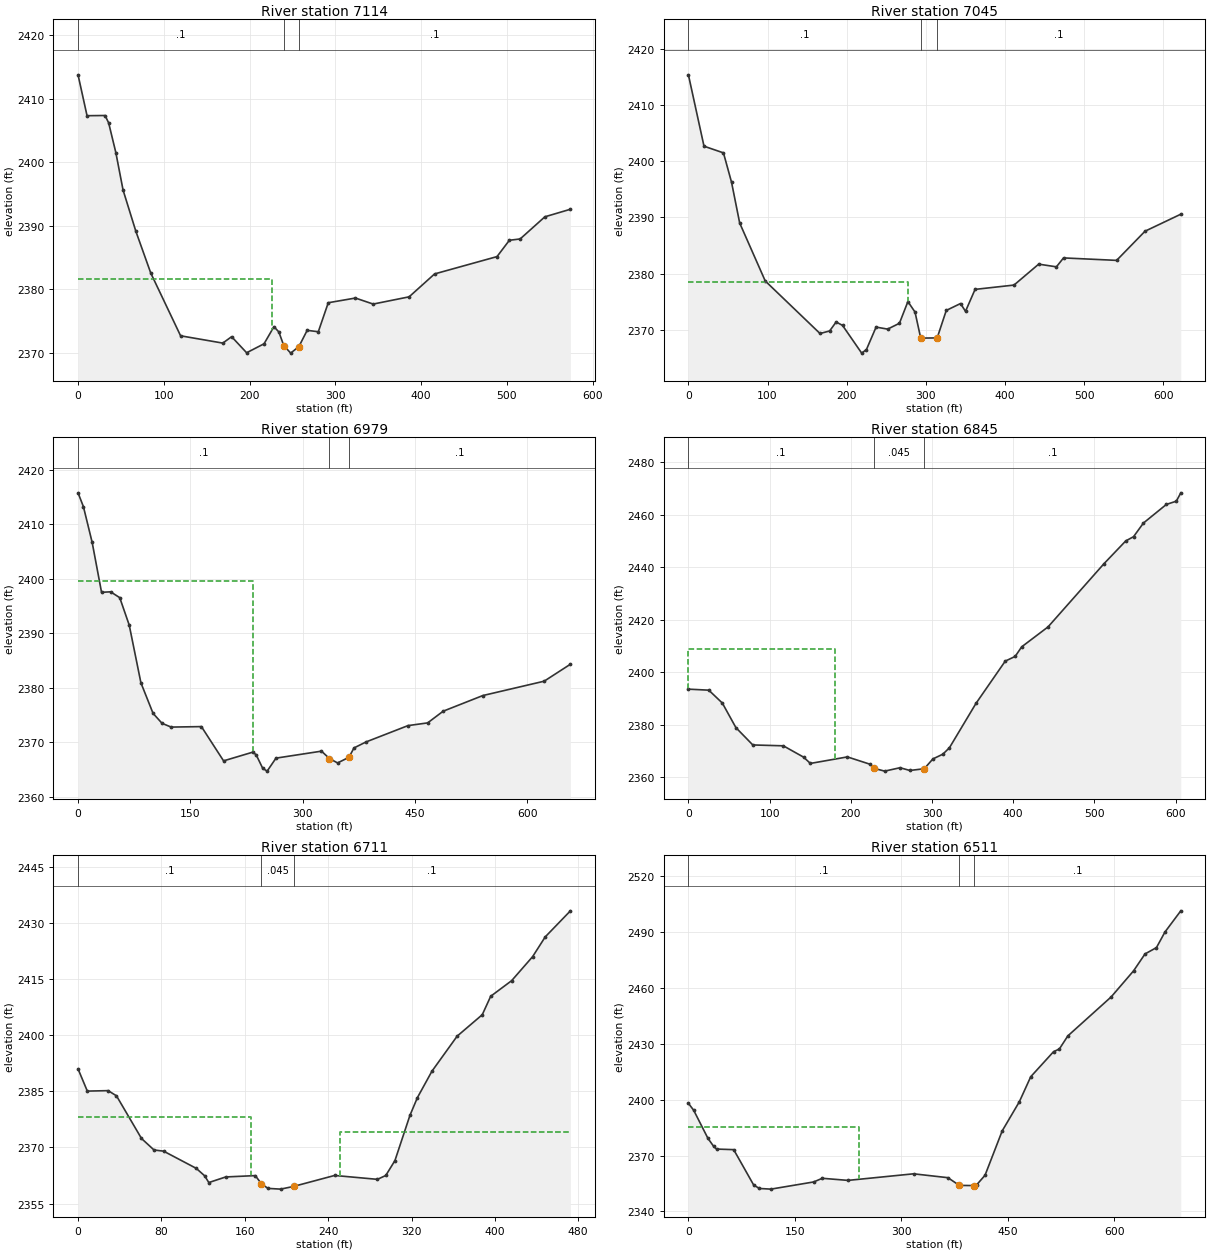
Type RM Length L Ch R = 1 ,7114    ,69.4,68.7,66.2
XS GIS Cut Line= 4
2256363.78259102662995.1467668422256402.06012462663115.804209689
2256491.09699624663189.0307956922256767.36093434663373.761501292
#Sta/Elev= 30
       0 2413.79    10.5 2407.35    31.5 2407.38    35.7 2406.22    44.1 2401.53
    52.5 2395.64    67.4 2389.15    84.8 2382.56   119.6 2372.67   168.8 2371.52
   179.1 2372.53   196.6    2370   216.9 2371.41   228.5 2374.11   234.2 2373.27
   239.9 2371.14     248 2369.94   257.6 2370.98   267.2 2373.53   280.2 2373.31
   291.8 2377.88   323.5 2378.62   344.2 2377.67   386.1 2378.81   415.8 2382.42
   488.6 2385.15     503 2387.72   515.6 2387.93   544.4 2391.42   574.2 2392.61
#Mann= 3, -1 ,  0
       0     0.1       0   239.9   0.045       0   257.6     0.1       0
#XS Ineff= 2 , 0
          225.89 2381.63
Permanent Ineff=
       F       F
Bank Sta=239.9,257.6
XS Rating Curve= 0 ,0
Exp/Cntr(USF)=0,0
Exp/Cntr=0.3,0.1

Type RM Length L Ch R = 1 ,7045    ,65.2,66.3,65.4
XS GIS Cut Line= 3
2256319.77267317663001.8242753862256356.75579742663195.985677668
2256736.84154813663385.305723341
#Sta/Elev= 30
       0 2415.42    19.7  2402.7    44.3 2401.51    54.5 2396.28    64.8 2389.01
    97.1 2378.68   166.3 2369.32   178.5 2369.77   186.7 2371.37   194.8 2370.76
     219 2365.82     225 2366.46   237.2 2370.46   251.8  2370.1   266.7 2371.14
   277.4 2375.01   286.4 2373.14   293.6  2368.5   314.4 2368.53   325.9 2373.43
   343.9 2374.66   350.2 2373.27   362.3 2377.18   411.5 2377.95   442.7 2381.68
   465.1  2381.2   474.1 2382.79   541.2 2382.35   577.1 2387.55   622.3 2390.58
#Mann= 3, -1 ,  0
       0     0.1       0   293.6   0.045       0   314.4     0.1       0
#XS Ineff= 2 , 0
          276.99 2378.54
Permanent Ineff=
       F       F
Bank Sta=293.6,314.4
XS Rating Curve= 0 ,0
Exp/Cntr(USF)=0,0
Exp/Cntr=0.3,0.1

Type RM Length L Ch R = 1 ,6979    ,122,133.3,155.9
XS GIS Cut Line= 3
 2256281.8623609663006.0753734762256315.66343715663241.187273967
2256682.39488358663446.300494894
#Sta/Elev= 30
       0 2415.75     7.2 2413.21    18.9 2406.65    31.4 2397.52    43.5 2397.61
    55.7 2396.54    68.4  2391.5      84 2380.93   100.2 2375.34   112.2 2373.51
   124.4 2372.82   164.8 2372.91   194.4 2366.63   233.5 2368.23   237.9 2367.75
   246.7 2365.26   252.6 2364.75   264.4 2367.13   325.2 2368.41   335.8 2367.06
   346.7 2366.25   361.9 2367.29   368.6    2369   384.9 2370.11   440.7 2373.09
     467 2373.59   487.7 2375.73   540.7  2378.6   622.6 2381.23   657.7 2384.34
#Mann= 3, -1 ,  0
       0     0.1       0   335.8   0.045       0   361.9     0.1       0
#XS Ineff= 2 , 0
           234.2 2399.57
Permanent Ineff=
       F       F
Bank Sta=335.8,361.9
XS Rating Curve= 0 ,0
Exp/Cntr(USF)=0,0
Exp/Cntr=0.3,0.1

Type RM Length L Ch R = 1 ,6845    ,126.4,134.8,127.3
XS GIS Cut Line= 3
2256245.89767493663049.1062033042256298.40457972663226.602370587
2256232.01558623663642.645566063
#Sta/Elev= 30
       0 2393.58    25.1 2393.19    41.8 2388.28    58.5 2378.94    79.3 2372.35
   116.9 2372.02   141.9  2367.7   150.2 2365.32   195.8  2367.8   224.2 2364.96
   228.2 2363.49   241.7 2362.39   260.6 2363.68   272.8 2362.64   290.42363.296
   301.1 2367.03   313.3 2368.83   321.4 2371.25   354.2 2388.18   390.2 2404.24
   402.4 2406.03   410.5 2409.69   442.9 2417.26   511.8 2441.31   538.6 2449.97
   548.2 2451.58   560.4 2456.78   588.7 2463.87   600.9 2465.09   606.4 2468.27
#Mann= 3, -1 ,  0
       0     0.1       0   228.2   0.045       0   290.4     0.1       0
#XS Ineff= 2 , 0
        180.0925  2408.7
Permanent Ineff=
       T       F
Bank Sta=228.2,290.4
XS Rating Curve= 0 ,0
Exp/Cntr(USF)=0,0
Exp/Cntr=0.3,0.1

Type RM Length L Ch R = 1 ,6711    ,200.2,199.9,193.6
XS GIS Cut Line= 4
2256156.48850774663060.3264332442256157.70173913 663133.72693239
2256184.99944542663304.1859428032256210.47730463663529.240365804
#Sta/Elev= 30
       0 2391.05     8.9  2385.1    28.9 2385.22    36.9 2383.83    60.9 2372.41
    72.9 2369.33    82.1 2369.02   113.4 2364.42   121.5 2362.42   125.5 2360.61
   141.7 2362.11   170.1 2362.47   175.9 2360.32   182.2 2359.05   194.4 2358.85
   206.92359.576   246.2 2362.51   287.3 2361.47   295.3  2362.5   304.1 2366.49
   318.5  2378.6   325.7 2383.37   339.6 2390.42   363.8 2399.81   387.9 2405.55
     396 2410.49   416.1 2414.67   436.2 2421.09   448.3 2426.38   472.5 2433.37
#Mann= 3, -1 ,  0
       0     0.1       0   175.9   0.045       0   206.9     0.1       0
#XS Ineff= 2 , 0
           166.2 2378.27  251.55         2374.24
Permanent Ineff=
       T       F
Bank Sta=175.9,206.9
XS Rating Curve= 0 ,0
Exp/Cntr(USF)=0,0
Exp/Cntr=0.3,0.1

Type RM Length L Ch R = 1 ,6511    ,249,252.6,252.1
XS GIS Cut Line= 2
2256008.13954756662993.7067684482256083.40865595663683.342440558
#Sta/Elev= 30
       0 2397.98     7.5  2394.2    27.6 2379.13    35.7 2374.84    39.7 2373.45
    63.8 2373.14      92 2354.15   100.1 2352.33   116.2 2351.98   176.5 2355.83
   188.6 2357.79   224.8 2356.66   317.3 2360.19   365.6 2358.11   381.7 2353.98
   402.2 2353.88   405.9 2354.19   417.9 2359.41   442.1 2383.21   466.2 2398.78
   482.3 2412.23   514.5 2425.67   522.6 2427.09   534.6 2434.12   595.6    2455
   627.2 2468.99   643.3 2478.04   659.4 2481.43   671.4 2489.79   693.7 2501.14
#Mann= 3, -1 ,  0
       0     0.1       0   381.7   0.045       0   402.2     0.1       0
#XS Ineff= 2 , 0
           239.8 2385.23
Permanent Ineff=
       F       F
Bank Sta=381.7,402.2
XS Rating Curve= 0 ,0
Exp/Cntr(USF)=0,0
Exp/Cntr=0.3,0.1

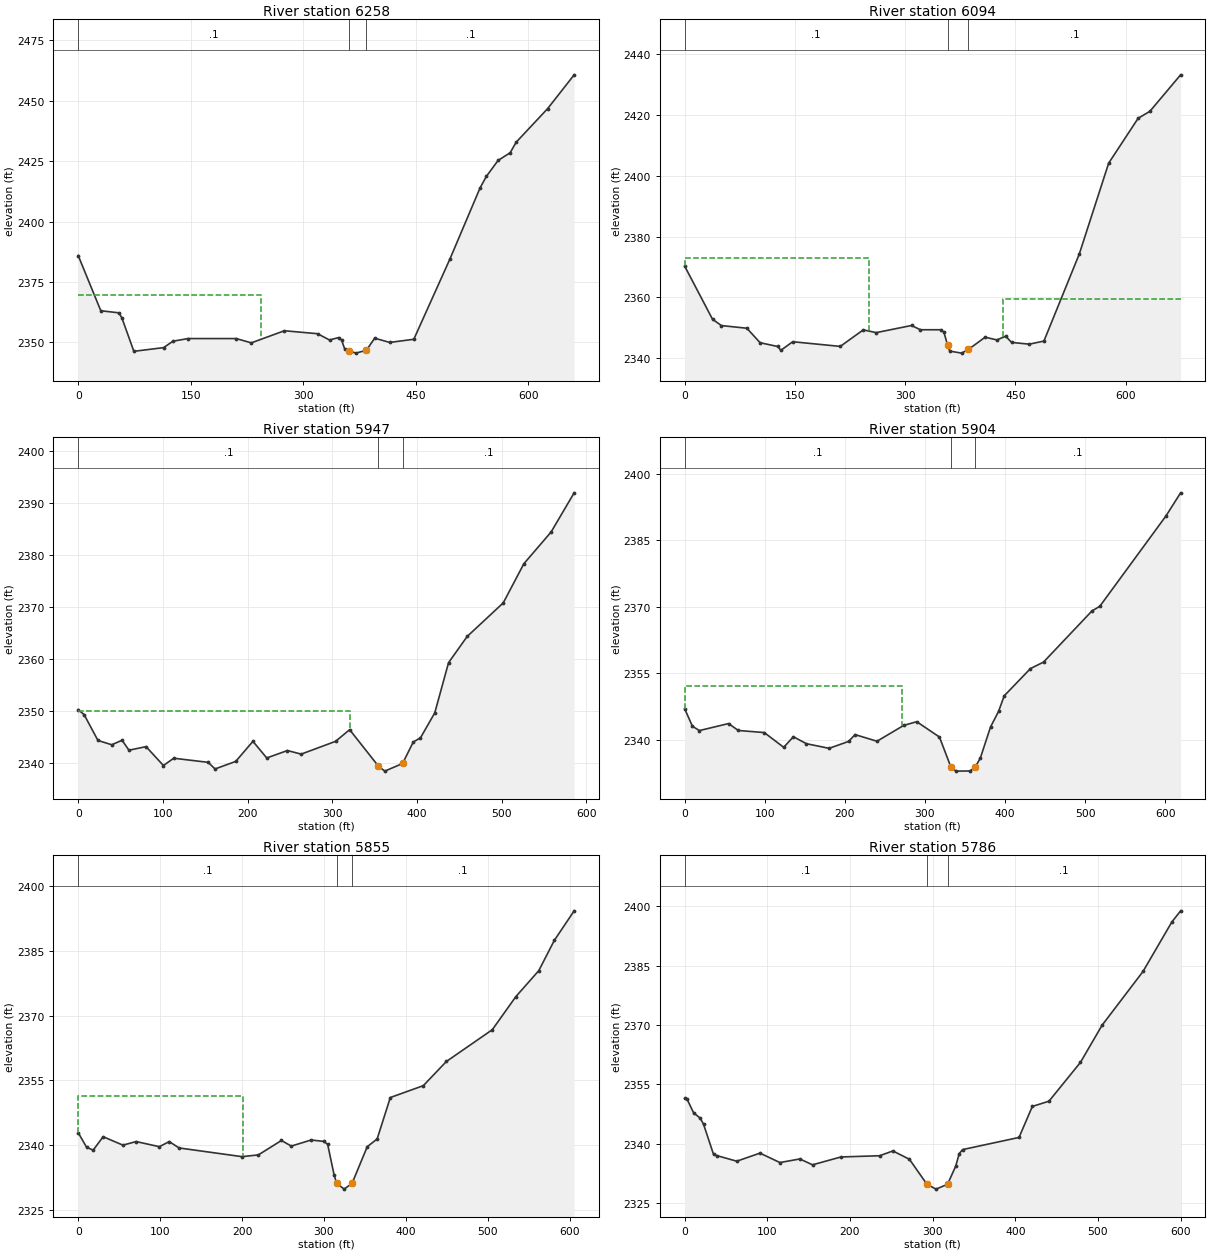
Type RM Length L Ch R = 1 ,6258    ,165.5,164.6,163.4
XS GIS Cut Line= 2
2255842.12388615662975.2116719262255786.93802864663634.253027825
#Sta/Elev= 30
       0 2385.91    30.1 2363.05    54.2 2362.19    58.2 2360.12    74.2 2346.25
   113.9 2347.78   126.4 2350.45   146.5 2351.53   210.7 2351.53   230.8 2349.75
   274.9 2354.77   319.1 2353.54   335.1 2350.94   347.2 2351.95   351.2 2350.94
   355.2 2347.34     3612346.471   370.3  2345.5   384.32346.696   395.3 2351.68
   415.4 2349.93   447.5 2351.24   495.7 2384.51   535.8 2413.89   544.4 2418.76
   559.9  2425.3     576 2428.49     584 2432.85   625.9 2446.74   661.3 2460.75
#Mann= 3, -1 ,  0
       0     0.1       0     361   0.045       0   384.3     0.1       0
#XS Ineff= 2 , 0
          243.75 2369.37
Permanent Ineff=
       F       F
Bank Sta=361,384.3
XS Rating Curve= 0 ,0
Exp/Cntr(USF)=0,0
Exp/Cntr=0.3,0.1

Type RM Length L Ch R = 1 ,6094    ,145,146.3,152.6
XS GIS Cut Line= 3
2255698.12616876662943.6771993732255654.67099777663242.315927645
2255638.02859186663614.920904406
#Sta/Elev= 30
       0 2370.28    37.9 2352.81      50 2350.73    84.6 2349.86   102.6  2345.1
   126.5 2343.85   130.9  2342.6     147 2345.42   211.7 2343.88     243 2349.32
   260.6 2348.41   308.7 2350.76   320.7 2349.36   348.7 2349.36   352.7 2348.55
   357.7 2344.32   360.7 2342.34   376.7 2341.67     386 2342.87   408.8 2346.91
   424.8 2346.01   436.8 2347.22   444.8 2345.19   468.8 2344.62   488.8 2345.63
   536.9 2374.25   576.9 2404.15     617 2418.91     633  2421.2   674.8  2433.2
#Mann= 3, -1 ,  0
       0     0.1       0   357.7   0.045       0     386     0.1       0
#XS Ineff= 2 , 0
          251.27 2373.04   433.3         2359.47
Permanent Ineff=
       F       F
Bank Sta=357.7,386
XS Rating Curve= 0 ,0
Exp/Cntr(USF)=0,0
Exp/Cntr=0.3,0.1

Type RM Length L Ch R = 1 ,5947    ,49.7,42.9,49.9
XS GIS Cut Line= 4
2255578.54112347662978.2798446692255518.43614995663304.703069611
2255488.77938262663392.9993541662255467.21082456663552.067469854
#Sta/Elev= 30
       0 2350.18       7 2349.22    23.3 2344.26    39.6 2343.43    51.8  2344.3
    59.9 2342.38    80.1 2343.07   100.6 2339.44   112.8 2340.84   153.4 2340.05
   161.6 2338.78     186 2340.23   206.3 2344.09   222.6 2340.89     247 2342.32
   263.3 2341.63   303.9 2344.09   320.5 2346.33   354.5 2339.32     362 2338.36
     383 2339.83   395.7 2343.98   404.1 2344.75     421 2349.56   437.3 2359.22
   459.3 2364.26   501.9 2370.72   526.2 2378.24   558.4 2384.35   585.6 2391.88
#Mann= 3, -1 ,  0
       0     0.1       0   354.5   0.045       0     383     0.1       0
#XS Ineff= 2 , 0
          321.19 2349.83
Permanent Ineff=
       F       F
Bank Sta=354.5,383
XS Rating Curve= 0 ,0
Exp/Cntr(USF)=0,0
Exp/Cntr=0.3,0.1

Type RM Length L Ch R = 1 ,5904    ,50.5,49.7,47
XS GIS Cut Line= 4
2255537.10004776662959.0320446612255487.17283003663271.909275767
2255453.88801821663363.4425082712255430.58864994663567.311980668
#Sta/Elev= 30
       0 2347.03     9.7 2343.09    18.4 2342.12    54.8  2343.7      67 2342.14
    99.4 2341.67   123.7 2338.34   135.8 2340.73     152 2339.16   180.4 2338.11
   204.7 2339.67   212.8 2341.21   240.2 2339.71   273.6 2343.29   289.8 2344.12
   318.2 2340.66   332.62333.833   338.9 2332.97   356.5 2333.01   362.82333.853
   369.3 2335.94     382 2342.93     392 2346.44   399.1 2349.96   431.8  2356.1
   448.2 2357.57   508.6 2369.09   518.5 2370.16   601.2 2390.56   619.4 2395.75
#Mann= 3, -1 ,  0
       0     0.1       0   332.6   0.045       0   362.8     0.1       0
#XS Ineff= 2 , 0
          271.45 2352.07
Permanent Ineff=
       F       F
Bank Sta=332.6,362.8
XS Rating Curve= 0 ,0
Exp/Cntr(USF)=0,0
Exp/Cntr=0.3,0.1

Type RM Length L Ch R = 1 ,5855    ,71,68.9,69.2
XS GIS Cut Line= 3
2255472.34876106662959.001225391 2255443.8574758663184.664750173
2255400.30686781663560.125029587
#Sta/Elev= 30
       0 2342.88    10.3 2339.49    18.3 2338.85    30.4 2341.95    54.6    2340
    70.7 2340.83      99 2339.64   111.1 2340.82   123.1 2339.35   199.8 2337.34
   219.9 2337.74   248.1 2341.08   260.1 2339.78   284.3 2341.19   299.8 2340.87
   304.5 2340.18   312.5    2333   315.62331.175   324.6 2329.82   334.32331.163
   352.8 2339.63   364.9 2341.43     381 2351.02   421.3 2353.77   449.4 2359.36
   505.5 2366.72   534.3 2374.39   562.2 2380.38   581.2 2387.39   605.4 2394.23
#Mann= 3, -1 ,  0
       0     0.1       0   315.6   0.045       0   334.3     0.1       0
#XS Ineff= 2 , 0
          201.41 2351.36
Permanent Ineff=
       F       F
Bank Sta=315.6,334.3
XS Rating Curve= 0 ,0
Exp/Cntr(USF)=0,0
Exp/Cntr=0.3,0.1

Type RM Length L Ch R = 1 ,5786    ,108.8,110.1,110.3
XS GIS Cut Line= 2
2255395.61854117662954.4634480282255338.57545702663551.745698351
#Sta/Elev= 30
       0 2351.46     2.7 2351.37    10.8 2347.84    18.8 2346.49    22.8 2344.97
    34.9 2337.35    38.9 2337.04      63 2335.62    91.1 2337.66   115.2 2335.28
   139.3 2336.19   154.7 2334.71     189 2336.69   235.8    2337   251.9 2338.21
   271.9 2336.11   293.22329.775   304.1 2328.57     3182329.791   327.9 2334.37
   332.2 2337.55   336.2 2338.55   404.5 2341.62   420.6 2349.45   440.7 2350.77
   478.8 2360.57     505 2369.96   554.5 2383.53   589.4 2396.03     600 2398.84
#Mann= 3, -1 ,  0
       0     0.1       0   293.2   0.045       0     318     0.1       0
Bank Sta=293.2,318
XS Rating Curve= 0 ,0
Exp/Cntr(USF)=0,0
Exp/Cntr=0.3,0.1

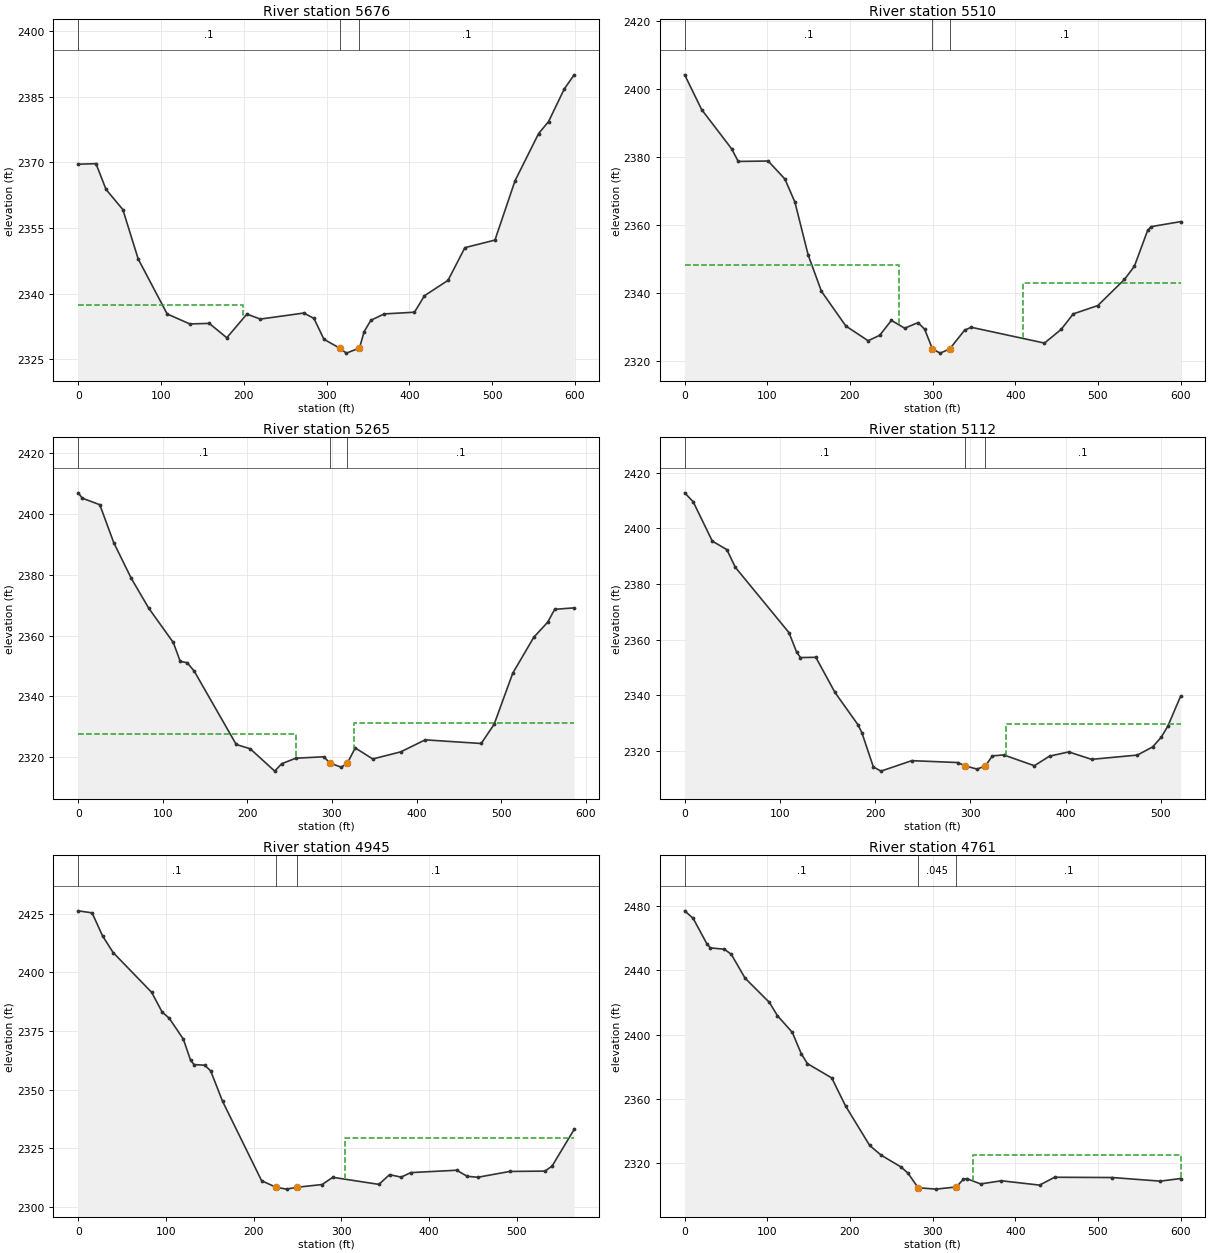
Type RM Length L Ch R = 1 ,5676    ,166.4,166.1,166.5
XS GIS Cut Line= 2
2255310.03393799662919.9634831332255215.52150937 663511.69347104
#Sta/Elev= 30
       0 2369.55    21.5 2369.68    33.6  2363.8    53.9 2359.21    72.5 2347.91
   107.5 2335.37   134.9  2333.1   158.3 2333.23   179.5 2329.95   203.8 2335.35
     220 2334.21   272.6 2335.59   284.8 2334.37   296.9  2329.6     3162327.571
     324 2326.44   339.8  2327.6   345.5 2331.37   353.6 2333.94   369.8 2335.39
   406.3 2335.78   418.3 2339.53   446.8 2343.05   467.2 2350.51   503.5 2352.24
   527.8 2365.79   556.2 2376.53   568.3 2379.29   587.3 2386.74   599.2 2389.95
#Mann= 3, -1 ,  0
       0     0.1       0     316   0.045       0   339.8     0.1       0
#XS Ineff= 2 , 0
          198.76 2337.41
Permanent Ineff=
       F       F
Bank Sta=316,339.8
XS Rating Curve= 0 ,0
Exp/Cntr(USF)=0,0
Exp/Cntr=0.3,0.1

Type RM Length L Ch R = 1 ,5510    ,247.5,244.2,239.7
XS GIS Cut Line= 2
2255149.69701017662856.8421798742255079.45444439663452.716312516
#Sta/Elev= 30
       0 2404.08    20.5 2393.89    56.7  2382.4    64.8 2378.66     101 2378.78
   121.2 2373.51   133.3 2366.77   149.4  2351.2   165.5 2340.52     195 2330.35
   221.9 2326.03   235.9 2327.62   250.1    2332   266.2  2329.7   282.3 2331.35
   290.3 2329.42   299.82323.596   309.1 2322.39   320.62323.609   338.7 2329.14
   346.7 2329.98   435.3 2325.34   455.5 2329.36   470.1 2333.91   499.8 2336.35
     532 2344.01   544.1  2347.9   560.1 2358.42   564.2 2359.51     600 2360.99
#Mann= 3, -1 ,  0
       0     0.1       0   299.8   0.045       0   320.6     0.1       0
#XS Ineff= 2 , 0
          259.47 2348.27  408.71         2343.12
Permanent Ineff=
       F       F
Bank Sta=299.8,320.6
XS Rating Curve= 0 ,0
Exp/Cntr(USF)=0,0
Exp/Cntr=0.3,0.1

Type RM Length L Ch R = 1 ,5265    ,149.5,153,157.3
XS GIS Cut Line= 2
2254807.86218666662928.5469076422254957.63394148663495.353964671
#Sta/Elev= 30
       0 2406.97     4.8 2405.21    25.5 2403.06      42 2390.59    62.7 2378.85
    83.4 2369.01   112.4 2357.73   120.6 2351.52   128.9 2351.08   137.2 2348.28
   186.8 2324.18   203.4 2322.76   232.3 2315.41   240.6 2317.86   257.2 2319.66
   290.3 2320.13   297.62318.091     311 2316.69   318.2 2318.05   327.5 2323.05
   348.2 2319.41   381.3 2321.75   410.2  2325.7   476.4  2324.5   491.7 2330.82
   513.7 2347.62   538.5 2359.41   555.1 2364.45   563.3 2368.65   586.3 2369.12
#Mann= 3, -1 ,  0
       0     0.1       0   297.6   0.045       0   318.2     0.1       0
#XS Ineff= 2 , 0
          257.43 2327.59  326.39         2331.26
Permanent Ineff=
       F       F
Bank Sta=297.6,318.2
XS Rating Curve= 0 ,0
Exp/Cntr(USF)=0,0
Exp/Cntr=0.3,0.1

Type RM Length L Ch R = 1 ,5112    ,173.3,167.7,173.5
XS GIS Cut Line= 4
2254732.18042574662944.3302624392254752.40094892663128.561695863
2254735.17605881663267.1097250652254723.94243482663462.574782479
#Sta/Elev= 30
       0 2412.81     8.9 2409.62      29 2395.44    44.3 2392.36    53.2 2385.99
   109.5  2362.5   117.6 2355.42   121.6 2353.52   137.7 2353.61   157.8 2340.96
   181.9 2329.36     186 2326.51   198.1 2314.16   206.1 2312.64   238.4 2316.41
   286.7 2315.73   294.8  2314.5   306.9 2313.38  315.74  2314.5     323 2318.13
     335 2318.47   367.1 2314.59   383.1 2318.04   403.2 2319.56   427.2 2316.88
   475.3 2318.42   491.3 2321.35   500.3 2324.82   507.3 2328.85   520.7 2339.63
#Mann= 3, -1 ,  0
       0     0.1       0   294.8   0.045       0  315.74     0.1       0
#XS Ineff= 2 , 0
                          337.01         2329.55
Permanent Ineff=
       F       F
Bank Sta=294.8,315.74
XS Rating Curve= 0 ,0
Exp/Cntr(USF)=0,0
Exp/Cntr=0.3,0.1

Type RM Length L Ch R = 1 ,4945    ,192.3,183.9,184.1
XS GIS Cut Line= 4
2254603.93213955662933.3575883822254605.60000655663044.040601785
2254569.54146041663255.7689880842254599.85857983663494.049408721
#Sta/Elev= 30
       0 2426.17    15.8 2425.31    27.8 2415.47    39.8 2408.41    83.8 2391.44
    95.8 2383.02   103.8 2380.43   119.9 2371.53   128.1 2362.63   132.1 2360.68
   144.3 2360.41   151.1 2357.99   164.6 2345.08   209.2  2311.2   225.5 2308.43
   237.6 2307.62   249.8 2308.43   278.2 2309.58   290.4 2312.65     343 2309.64
   355.1 2313.78   368.4 2312.73   379.3 2314.66   431.7 2315.67   443.8 2313.07
   455.9 2312.68   492.2 2315.15   532.5  2315.3   540.6 2317.48   565.7 2333.08
#Mann= 3, -1 ,  0
       0     0.1       0   225.5   0.045       0   249.8     0.1       0
#XS Ineff= 2 , 0
                          304.58         2329.37
Permanent Ineff=
       F       F
Bank Sta=225.5,249.8
XS Rating Curve= 0 ,0
Exp/Cntr(USF)=0,0
Exp/Cntr=0.3,0.1

Type RM Length L Ch R = 1 ,4761    ,251.9,250,247.4
XS GIS Cut Line= 2
2254321.44063508662919.3617206932254500.00170901663492.175776802
#Sta/Elev= 30
       0 2476.96    10.3 2472.25      27 2456.32    31.2 2453.92      48 2453.09
    56.4 2449.91    73.1 2435.09   102.5 2420.03   112.2  2411.8   130.2 2401.42
     141 2388.18   148.5 2381.98   177.9 2373.11   194.6 2355.71   223.8 2331.13
   237.7 2325.09   261.7 2317.76   270.1 2313.95   282.42304.859   303.9 2303.98
   328.7 2305.33   337.1  2310.1   341.3 2310.51     358 2307.22   383.2 2309.17
   429.3 2306.48   447.6 2311.36   517.3 2311.19   575.4 2308.94     600 2310.58
#Mann= 3, -1 ,  0
       0     0.1       0   282.4   0.045       0   328.7     0.1       0
#XS Ineff= 2 , 0
                          348.67         2325.33
Permanent Ineff=
       F       F
Bank Sta=282.4,328.7
XS Rating Curve= 0 ,0
Exp/Cntr(USF)=0,0
Exp/Cntr=0.3,0.1