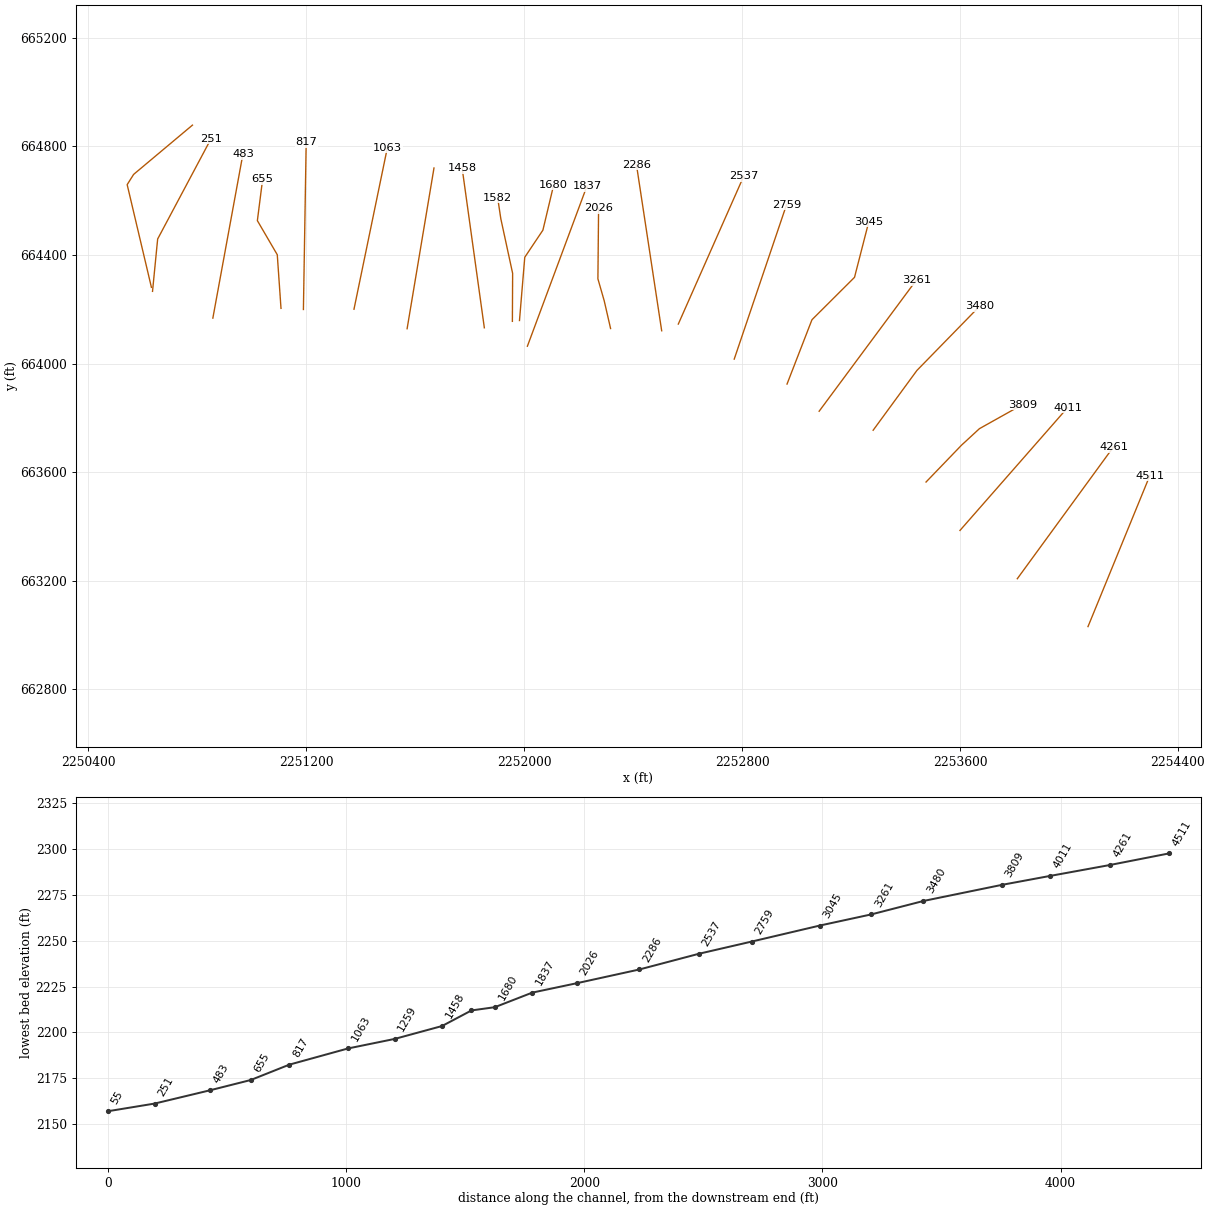
HEC-RAS study PNTHRNT1.prj: PNTHRNT1

--- PNTHRNT1.g01 (geometry) --- (continued)

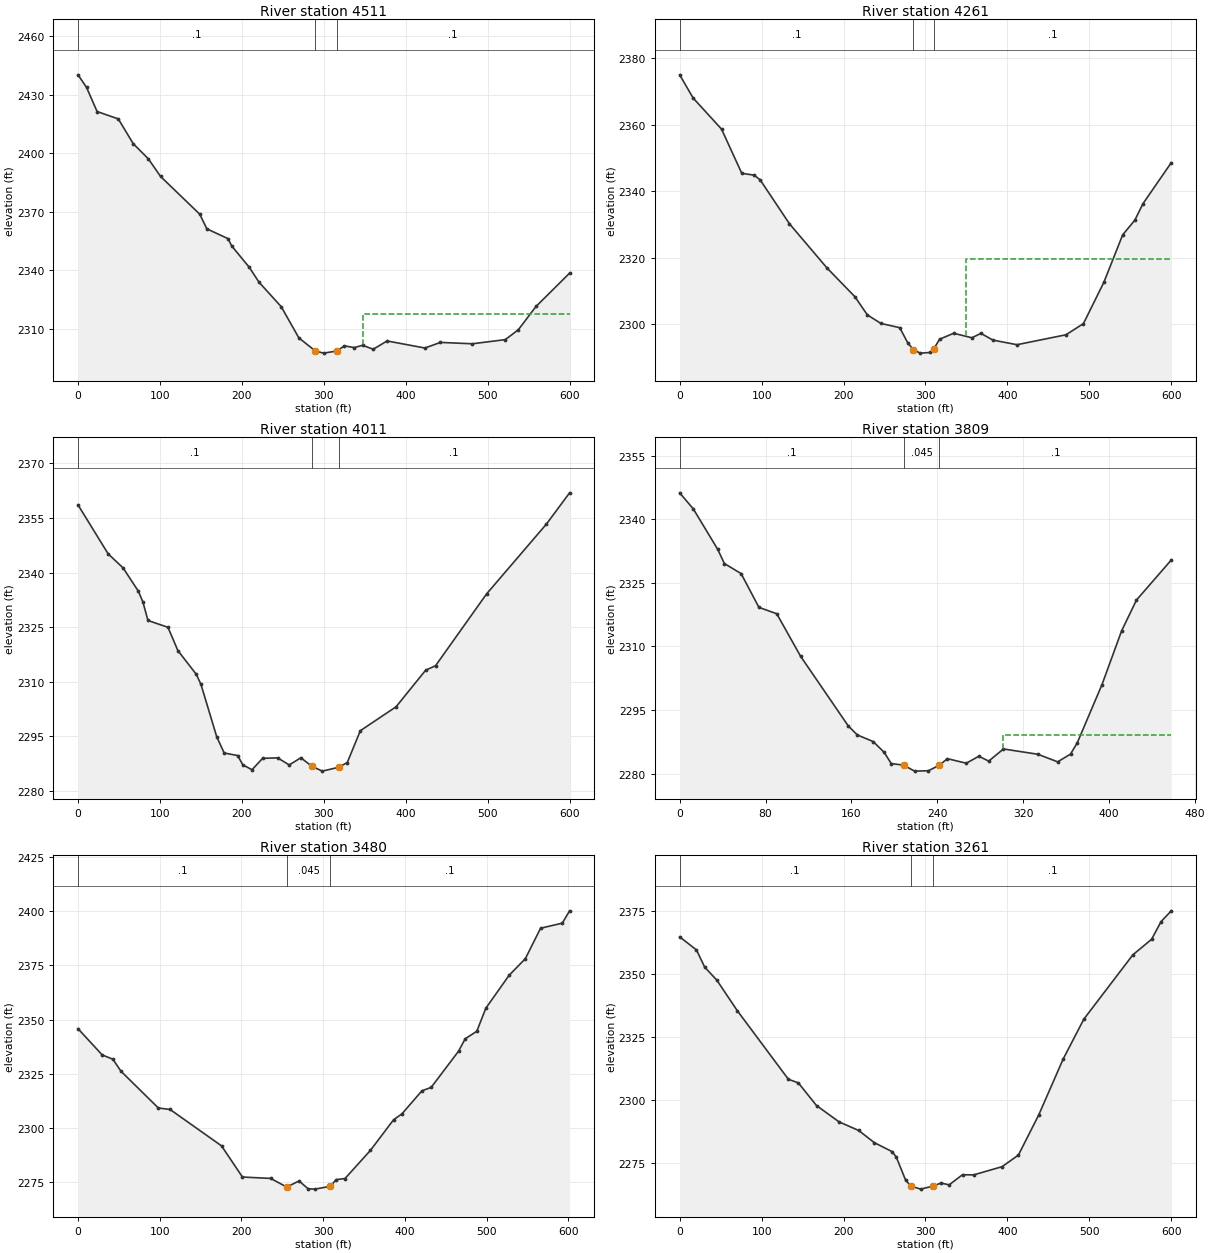
Type RM Length L Ch R = 1 ,4511    ,251.6,250,245.3
XS GIS Cut Line= 2
2254069.84710362663031.5796663132254296.52697414 663587.11205628
#Sta/Elev= 30
       0 2440.07    10.4 2433.68    23.3 2421.31    49.2 2417.51    67.4 2404.87
    85.9 2397.09   100.8 2388.09   148.6 2368.79   157.3  2361.3   183.2 2356.27
   187.5 2352.61   209.1  2341.6   220.9 2334.03     248 2321.51   269.6 2305.53
   289.82298.805   299.8 2297.74   315.62298.804   325.2 2301.45   337.4 2300.57
   347.3 2301.77   360.3 2299.72   377.3 2303.96   423.4 2300.36   442.4 2303.22
   481.3 2302.52   521.5 2304.64   537.4 2309.67     559 2321.59     600 2338.64
#Mann= 3, -1 ,  0
       0     0.1       0   289.8   0.045       0   315.6     0.1       0
#XS Ineff= 2 , 0
                          347.31         2317.76
Permanent Ineff=
       F       F
Bank Sta=289.8,315.6
XS Rating Curve= 0 ,0
Exp/Cntr(USF)=0,0
Exp/Cntr=0.3,0.1

Type RM Length L Ch R = 1 ,4261    ,251.2,250,249.4
XS GIS Cut Line= 2
2253810.34674998663207.866322704 2254163.2498882663693.107886295
#Sta/Elev= 30
       0 2374.92    16.5 2367.93    51.1 2358.62    75.8 2345.35      91  2344.8
    98.3 2343.36     134  2330.2   179.9 2316.91   213.9  2308.3   229.1 2302.84
   245.6 2300.29   268.6 2299.01   278.6 2294.35   285.32292.452   293.4 2291.37
   305.8 2291.56   309.82292.471   317.2 2295.54   334.4 2297.33   356.7 2295.98
   367.6  2297.3   382.5 2295.27   411.7  2293.9   471.5 2296.88   492.8 2300.23
   517.7 2312.61   540.7 2326.88   555.6 2331.31   565.5 2336.25     600 2348.55
#Mann= 3, -1 ,  0
       0     0.1       0   285.3   0.045       0   309.8     0.1       0
#XS Ineff= 2 , 0
                          349.69         2319.57
Permanent Ineff=
       F       F
Bank Sta=285.3,309.8
XS Rating Curve= 0 ,0
Exp/Cntr(USF)=0,0
Exp/Cntr=0.3,0.1

Type RM Length L Ch R = 1 ,4011    ,202,201.9,198.3
XS GIS Cut Line= 2
2253599.95733071663385.6677965932253994.70067702663837.528052141
#Sta/Elev= 30
       0 2358.62    36.8 2345.16      55  2341.3    73.7 2334.89    79.2 2331.95
    85.4 2326.84   109.8 2324.97   121.9 2318.58   144.4 2312.04   150.1 2309.27
   169.3  2294.9   178.4 2290.43   194.9 2289.72   201.2 2287.15   212.4 2285.82
   225.3 2288.95   243.7 2289.09   257.8 2287.14     272 2289.11   285.72286.736
   298.2 2285.44   318.32286.504   328.7 2287.81   344.6 2296.55   388.2 2303.12
   424.3 2313.17   436.4 2314.41   498.7 2334.15   571.8 2353.36     600 2361.93
#Mann= 3, -1 ,  0
       0     0.1       0   285.7   0.045       0   318.3     0.1       0
Bank Sta=285.7,318.3
XS Rating Curve= 0 ,0
Exp/Cntr(USF)=0,0
Exp/Cntr=0.3,0.1

Type RM Length L Ch R = 1 ,3809    ,317,329.2,326.1
XS GIS Cut Line= 4
2253475.38469977 663563.936429742253605.52097997663699.531897976
2253671.31739107663760.4304368952253828.40256343663848.641684151
#Sta/Elev= 30
       0 2346.25    12.7 2342.45    35.4 2332.93    41.6 2329.57    57.2 2327.19
    73.8 2319.22    90.4 2317.71   112.6 2307.68   157.1  2291.2   165.5  2289.1
   180.2 2287.55   190.4 2285.02     197 2282.36  208.61 2281.97   218.8 2280.57
   231.6 2280.66   241.9 2281.97   249.3 2283.51   266.9 2282.44   278.6 2284.08
   287.8 2282.94   301.5  2285.8   333.6 2284.55     352 2282.76     364 2284.59
   370.3 2287.28   393.3    2301   411.6  2313.7   425.4 2320.95   457.8 2330.39
#Mann= 3, -1 ,  0
       0     0.1       0  208.61   0.045       0   241.9     0.1       0
#XS Ineff= 2 , 0
                             301         2289.05
Permanent Ineff=
       F       F
Bank Sta=208.61,241.9
XS Rating Curve= 0 ,0
Exp/Cntr(USF)=0,0
Exp/Cntr=0.3,0.1

Type RM Length L Ch R = 1 ,3480    ,206.2,218.8,220.4
XS GIS Cut Line= 3
2253281.27927554663754.6581623032253441.84570855663974.769982837
2253671.29534439664210.604942139
#Sta/Elev= 30
       0  2345.8    29.6 2333.69    42.7 2331.71    52.5  2326.2    98.3 2309.21
   112.7 2308.52   175.6 2291.75   201.2 2277.36   235.8 2276.72   255.42272.742
   270.5 2275.55   281.5 2271.96   289.9 2271.78   308.72273.086   315.9 2276.16
   326.7 2276.67   357.8 2289.65   386.1 2303.77   396.3 2306.47   420.9 2317.17
   432.1 2318.69   465.6 2335.39   473.8 2341.14     488 2344.61     499 2355.23
   527.6 2370.47   547.4  2378.1     566 2392.13   592.6 2394.48   601.5 2400.16
#Mann= 3, -1 ,  0
       0     0.1       0   255.4   0.045       0   308.7     0.1       0
Bank Sta=255.4,308.7
XS Rating Curve= 0 ,0
Exp/Cntr(USF)=0,0
Exp/Cntr=0.3,0.1

Type RM Length L Ch R = 1 ,3261    ,219.8,215.8,215
XS GIS Cut Line= 2
2253083.09786934663824.6496677722253439.58463157664307.264616109
#Sta/Elev= 30
       0 2364.56    20.5 2359.37    30.5 2352.56    45.4 2347.36    70.3 2335.28
   132.7 2308.04   144.9 2306.61     167 2297.63   194.6 2291.14   218.5 2287.73
   237.4 2282.94   259.2 2279.35   264.3 2277.24   275.7 2268.08   282.12265.705
   294.1 2264.46   309.72265.706   318.9 2266.89   328.9 2266.16   345.2 2270.18
   358.7  2270.1   393.5 2273.37   413.4 2277.96   438.3 2293.95   468.1 2316.11
   493.3 2331.91   553.2 2357.46     576 2363.59   587.5 2370.59     600 2374.89
#Mann= 3, -1 ,  0
       0     0.1       0   282.1   0.045       0   309.7     0.1       0
Bank Sta=282.1,309.7
XS Rating Curve= 0 ,0
Exp/Cntr(USF)=0,0
Exp/Cntr=0.3,0.1

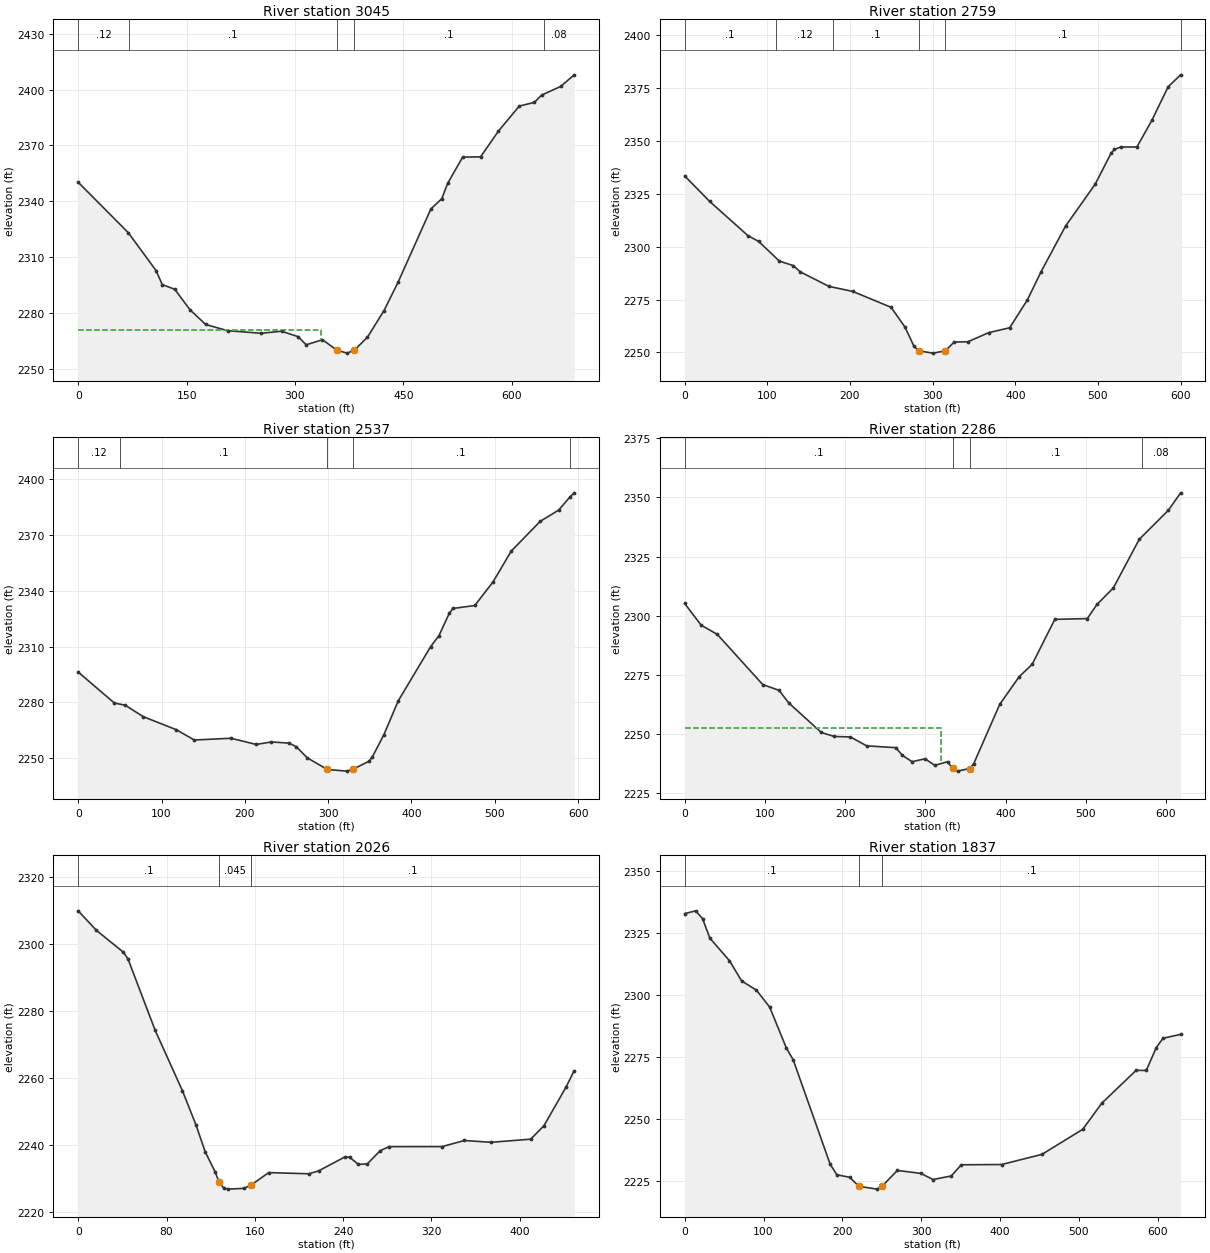
Type RM Length L Ch R = 1 ,3045    ,281.8,286.4,291.3
XS GIS Cut Line= 4
 2252965.1692699663924.6470317512253056.62388343 664161.44750654
2253212.87758337664317.7012064742253265.36059382664522.638395267
#Sta/Elev= 30
       0 2350.17    69.2 2323.13   107.8 2302.71   116.3 2295.21   133.5 2292.72
   154.9 2281.59   176.4 2273.78   206.9 2270.43   253.3 2269.04   281.5 2270.15
   304.3 2267.23   315.6 2262.86   338.1 2265.58     358 2259.99     372 2258.38
  382.15 2259.94   400.3 2266.92   423.2 2281.22   442.8 2296.56   488.1 2335.86
   503.2 2341.36   511.4 2349.66   532.1 2363.67   556.9 2363.84   581.6 2377.66
   610.5 2391.13   631.2 2393.07   641.5 2397.03   667.8 2401.67   686.4  2407.9
#Mann= 5, -1 ,  0
       0    0.12       0      70     0.1       0     358   0.045       0
  382.15     0.1       0  644.82    0.08       0
#XS Ineff= 2 , 0
          335.39 2270.55
Permanent Ineff=
       F       F
Bank Sta=358,382.15
XS Rating Curve= 0 ,0
Exp/Cntr(USF)=0,0
Exp/Cntr=0.3,0.1

Type RM Length L Ch R = 1 ,2759    ,223.8,221.6,220.4
XS GIS Cut Line= 2
2252771.42493705664016.6044069132252963.35350789664585.079053398
#Sta/Elev= 30
       0 2333.52    30.2 2321.46    76.6 2305.22    89.4 2302.54   114.6 2293.19
   131.5 2291.05   139.9 2288.09   174.6 2281.22   203.3 2278.85   249.7 2271.32
   266.6 2261.92   277.4 2252.89   283.12250.693   300.4 2249.63   315.12250.694
   326.1 2254.88   342.6 2255.01   367.9 2259.34   393.2 2261.64   414.5 2274.75
   431.2 2288.19   460.8 2309.79   496.6 2329.57   515.7 2344.16   519.9 2346.06
   527.5 2347.21   547.1 2347.21   565.1 2359.75   584.9 2375.71     600 2381.37
#Mann= 6, -1 ,  0
       0     0.1       0     110    0.12       0     180     0.1       0
   283.1   0.045       0   315.1     0.1       0     600    0.08       0
Bank Sta=283.1,315.1
XS Rating Curve= 0 ,0
Exp/Cntr(USF)=0,0
Exp/Cntr=0.3,0.1

Type RM Length L Ch R = 1 ,2537    ,244.1,250.5,258.1
XS GIS Cut Line= 2
2252566.13763577664145.6038380772252806.29888713664690.279108005
#Sta/Elev= 30
       0 2296.26    43.3 2279.64    56.4 2278.42    78.2 2272.25   117.6 2265.28
   139.4 2259.71   183.3 2260.65   213.7 2257.33   231.8 2258.67   253.1 2258.03
   261.8 2256.08   274.9 2250.13     2992243.874   322.3 2242.97   329.32243.886
   349.3 2248.35   353.2 2250.73   366.7 2262.35   384.2 2280.82   422.9 2309.86
   433.1 2315.93   445.4 2327.87   449.8 2330.46     476 2332.07   497.9 2344.73
   519.8 2361.35   554.7 2377.39   576.6 2383.35     590 2390.31   595.3 2392.68
#Mann= 5, -1 ,  0
       0    0.12       0      50     0.1       0     299   0.045       0
   329.3     0.1       0     590    0.08       0
Bank Sta=299,329.3
XS Rating Curve= 0 ,0
Exp/Cntr(USF)=0,0
Exp/Cntr=0.3,0.1

Type RM Length L Ch R = 1 ,2286    ,269.7,260.8,267.7
XS GIS Cut Line= 2
2252505.12747529 664120.943861632252412.58935377664732.167475218
#Sta/Elev= 30
       0 2305.17    20.5 2296.03    40.7 2292.12    97.3 2270.93   117.6 2268.51
   129.7 2263.19   170.2 2250.73   186.3 2249.02   206.6 2248.82   226.8 2245.06
   263.2 2244.28   271.3 2241.07   283.4 2238.36   299.6 2239.59   311.7 2236.84
   327.9 2238.35   333.92235.499   340.1 2234.38   355.52235.482   360.3 2237.53
   392.7 2262.56   416.9 2274.23   433.2 2279.51   461.4 2298.46   501.9  2298.8
     514 2304.81   534.3 2311.71   566.6 2332.25     603 2344.55   618.2  2351.9
#Mann= 4, -1 ,  0
       0     0.1       0   333.9   0.045       0   355.5     0.1       0
     570    0.08       0
#XS Ineff= 2 , 0
          320.09 2252.65
Permanent Ineff=
       F       F
Bank Sta=333.9,355.5
XS Rating Curve= 0 ,0
Exp/Cntr(USF)=0,0
Exp/Cntr=0.3,0.1

Type RM Length L Ch R = 1 ,2026    ,202.1,188.8,183.9
XS GIS Cut Line= 4
2252317.59968549664129.2051793562252294.38469669664230.617814782
2252271.08532841664312.165603741 2252273.5816893664572.619256232
#Sta/Elev= 30
       0 2309.79    16.4    2304      41 2297.45    45.1 2295.47    69.7 2274.23
    94.4 2256.24   106.7 2246.06     115 2238.07   124.1 2232.05   127.5 2229.15
   131.7 2227.27   135.8 2226.94     150 2227.17   156.4  2228.1   172.6 2231.86
     209 2231.51   217.9 2232.39   241.9 2236.58   245.9  2236.4   253.9  2234.3
   261.9 2234.45   273.6  2238.4   281.7 2239.59   329.6  2239.6   349.9 2241.42
   373.9 2240.88   409.9 2241.81   421.9  2245.8   441.9 2257.27   449.3  2262.2
#Mann= 3, -1 ,  0
       0     0.1       0   127.5   0.045       0   156.4     0.1       0
Bank Sta=127.5,156.4
XS Rating Curve= 0 ,0
Exp/Cntr(USF)=0,0
Exp/Cntr=0.3,0.1

Type RM Length L Ch R = 1 ,1837    ,165,157.1,151.2
XS GIS Cut Line= 2
2252012.28973022664064.0899300282252230.92587824 664654.09273601
#Sta/Elev= 30
       0 2332.88      14 2334.01    22.7 2330.84    31.9 2323.02    56.8  2313.9
    72.3 2305.72      91 2302.01   107.8 2295.21   129.1 2278.61   137.7  2273.9
   184.6 2231.78   193.1 2227.55   209.3 2226.53   221.22222.858   244.3 2221.75
   250.22222.852   269.9 2229.29   299.6  2228.1   315.1 2225.62   338.2 2227.06
     351 2231.57   402.1 2231.68   453.3 2235.78     505 2245.87   529.2 2256.42
   572.8 2269.67   585.6 2269.61   598.3 2278.83   606.9  2282.6   629.2 2284.19
#Mann= 3, -1 ,  0
       0     0.1       0   221.2   0.045       0   250.2     0.1       0
Bank Sta=221.2,250.2
XS Rating Curve= 0 ,0
Exp/Cntr(USF)=0,0
Exp/Cntr=0.3,0.1

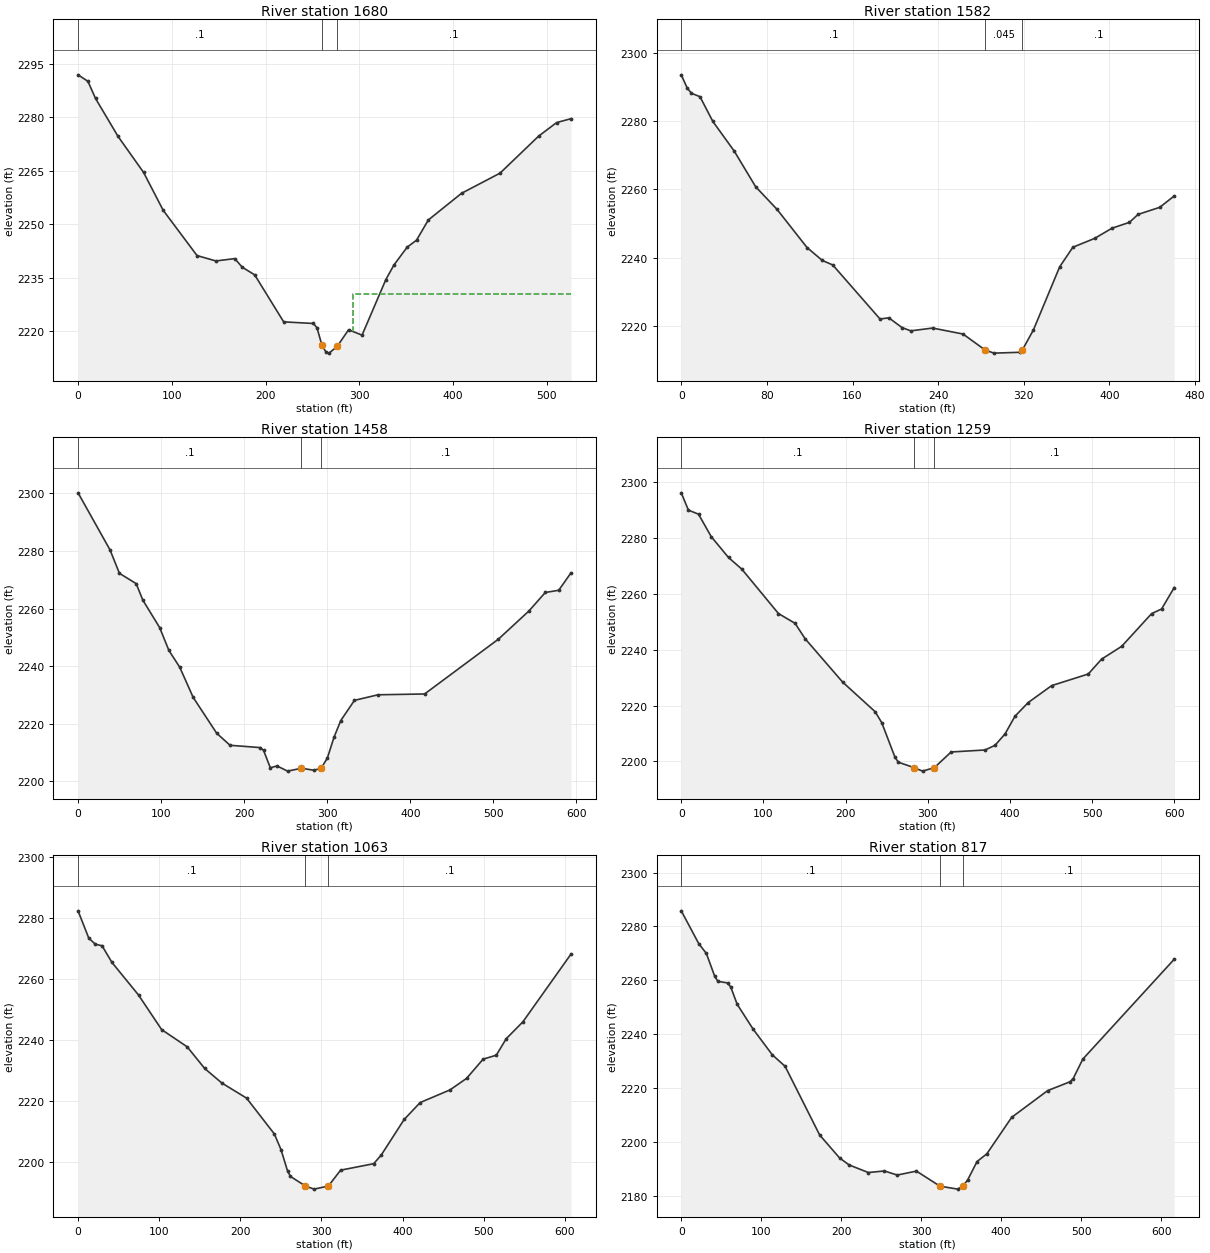
Type RM Length L Ch R = 1 ,1680    ,91,98,113.9
XS GIS Cut Line= 4
2251983.23886653664158.6820944162252002.65500675664391.675777155
2252069.22463039664491.5302126152252108.98148896664658.878849822
#Sta/Elev= 30
       0 2291.88    10.5 2290.06    18.6 2285.26    42.6 2274.62    69.9 2264.49
    90.8 2253.87   126.9 2241.17     147 2239.66   167.1 2240.32   175.1 2237.91
   188.4 2235.75   219.3 2222.57     251 2222.12   254.8 2220.93     2602216.143
   264.5 2214.05   267.7  2213.8   276.4 2215.69   288.5 2220.35   302.9 2218.85
   328.3 2234.44   336.9 2238.52     351 2243.53     361 2245.48   373.6 2251.16
     409 2258.64   450.1  2264.3   491.2 2274.67   510.4 2278.48   525.8 2279.58
#Mann= 3, -1 ,  0
       0     0.1       0     260   0.045       0   276.4     0.1       0
#XS Ineff= 2 , 0
                          293.31         2230.37
Permanent Ineff=
       F       F
Bank Sta=260,276.4
XS Rating Curve= 0 ,0
Exp/Cntr(USF)=0,0
Exp/Cntr=0.3,0.1

Type RM Length L Ch R = 1 ,1582    ,125.1,123.8,124.8
XS GIS Cut Line= 4
2251957.19599671664155.6409572132251958.12057482 664332.23537548
2251914.66540383664533.7934026122251903.18057289664610.638062557
#Sta/Elev= 30
       0 2293.49     5.5 2289.66     9.5 2288.09    17.5 2287.09    29.5 2279.85
    49.5 2271.16    69.5 2260.73    89.5  2254.1   117.5 2242.93   131.8 2239.15
   141.5 2237.84   185.7 2222.01   193.9 2222.37   206.2 2219.51   214.4 2218.55
   234.8 2219.37   263.2 2217.62     284 2212.91   292.1 2212.03   316.7 2212.28
   318.7 2212.98     329 2218.85   353.5 2237.29   365.8 2243.02   386.2 2245.62
   402.4  2248.6   418.6  2250.3   426.7 2252.63   446.9  2254.7   460.5 2258.03
#Mann= 3, -1 ,  0
       0     0.1       0     284   0.045       0   318.7     0.1       0
Bank Sta=284,318.7
XS Rating Curve= 0 ,0
Exp/Cntr(USF)=0,0
Exp/Cntr=0.3,0.1

Type RM Length L Ch R = 1 ,1458    ,203.2,198.7,196.1
XS GIS Cut Line= 2
2251854.23372199664131.8679861612251772.78348999664719.838098861
#Sta/Elev= 30
       0 2300.22    38.5 2280.38    49.8 2272.25      70 2268.66      78 2262.93
    98.2 2253.42   109.4 2245.44   122.5 2239.58   138.6 2229.14   166.9 2216.69
     183 2212.49   219.4 2211.69   223.4 2210.69   231.5 2204.68   239.6 2205.31
   252.3 2203.51     269 2204.51     284 2203.82  292.65 2204.49   300.2 2208.07
   308.2 2215.28   316.3 2221.07   332.8  2228.1   361.2 2230.04   417.3 2230.32
   506.1 2249.36   542.9 2259.16   562.6 2265.59   578.8 2266.36   593.6 2272.44
#Mann= 3, -1 ,  0
       0     0.1       0     269   0.045       0  292.65     0.1       0
Bank Sta=269,292.65
XS Rating Curve= 0 ,0
Exp/Cntr(USF)=0,0
Exp/Cntr=0.3,0.1

Type RM Length L Ch R = 1 ,1259    ,197.6,196.3,197.3
XS GIS Cut Line= 2
2251570.81636601664128.5057142362251669.45829749664720.341645347
#Sta/Elev= 30
       0 2296.28     8.7 2290.07      21 2288.63    36.5 2280.56    57.5 2273.09
    73.7 2268.92   118.3 2252.99   138.6 2249.47   150.7 2243.98   196.4 2228.41
   235.9 2217.82     244 2213.87   260.2 2201.41   264.3 2199.67   283.62197.712
   293.7 2196.48     3082197.719   328.5 2203.35   369.7 2204.06   381.9 2205.74
     394 2209.79   406.2 2216.17   422.3 2221.08   450.8 2227.14   495.4 2231.31
   511.6 2236.64     536 2241.22   572.5 2252.97   584.6 2254.62     600 2262.32
#Mann= 3, -1 ,  0
       0     0.1       0   283.6   0.045       0     308     0.1       0
Bank Sta=283.6,308
XS Rating Curve= 0 ,0
Exp/Cntr(USF)=0,0
Exp/Cntr=0.3,0.1

Type RM Length L Ch R = 1 ,1063    ,242.5,246.1,247.7
XS GIS Cut Line= 2
2251375.82134764664200.2536443842251498.41996298664795.379620491
#Sta/Elev= 30
       0 2282.39    13.2 2273.45    21.4 2271.43    29.5 2270.97    41.8 2265.48
    74.5 2254.83     103  2243.5   134.5 2237.86   156.1 2230.76   177.2 2226.01
   207.7 2221.06   241.9 2209.34   250.1 2204.23   258.2  2197.2   261.8 2195.41
   280.32192.273   290.9 2191.26   308.5 2192.27   323.6 2197.47   364.4 2199.59
   373.6 2202.39   401.9 2214.06   421.6  2219.6   458.4 2223.75   478.8 2227.51
   499.2 2233.81   515.5 2235.12   527.8 2240.54   548.2 2246.02   607.6 2268.24
#Mann= 3, -1 ,  0
       0     0.1       0   280.3   0.045       0   308.5     0.1       0
Bank Sta=280.3,308.5
XS Rating Curve= 0 ,0
Exp/Cntr(USF)=0,0
Exp/Cntr=0.3,0.1

Type RM Length L Ch R = 1 ,817     ,151.7,161.9,167.6
XS GIS Cut Line= 2
2251190.21033726664199.2613198712251200.41195558664815.472305267
#Sta/Elev= 30
       0 2285.79    21.9 2273.59    31.4 2269.95    41.9 2261.42    45.9 2259.58
    57.9 2259.02    61.9 2257.47    69.9 2251.08    89.9 2241.82   113.9 2232.29
   129.8 2228.05     173 2202.55   197.9 2194.02   209.9  2191.4   233.9  2188.6
     254 2189.17     270 2187.66     294 2189.12   323.52183.517   345.7 2182.43
     352 2183.51     358 2185.81   369.8 2192.68     382 2195.53   413.1 2209.09
     458 2219.01     486  2222.3     490  2223.5     502 2230.71   616.3 2267.81
#Mann= 3, -1 ,  0
       0     0.1       0   323.5   0.045       0     352     0.1       0
Bank Sta=323.5,352
XS Rating Curve= 0 ,0
Exp/Cntr(USF)=0,0
Exp/Cntr=0.3,0.1

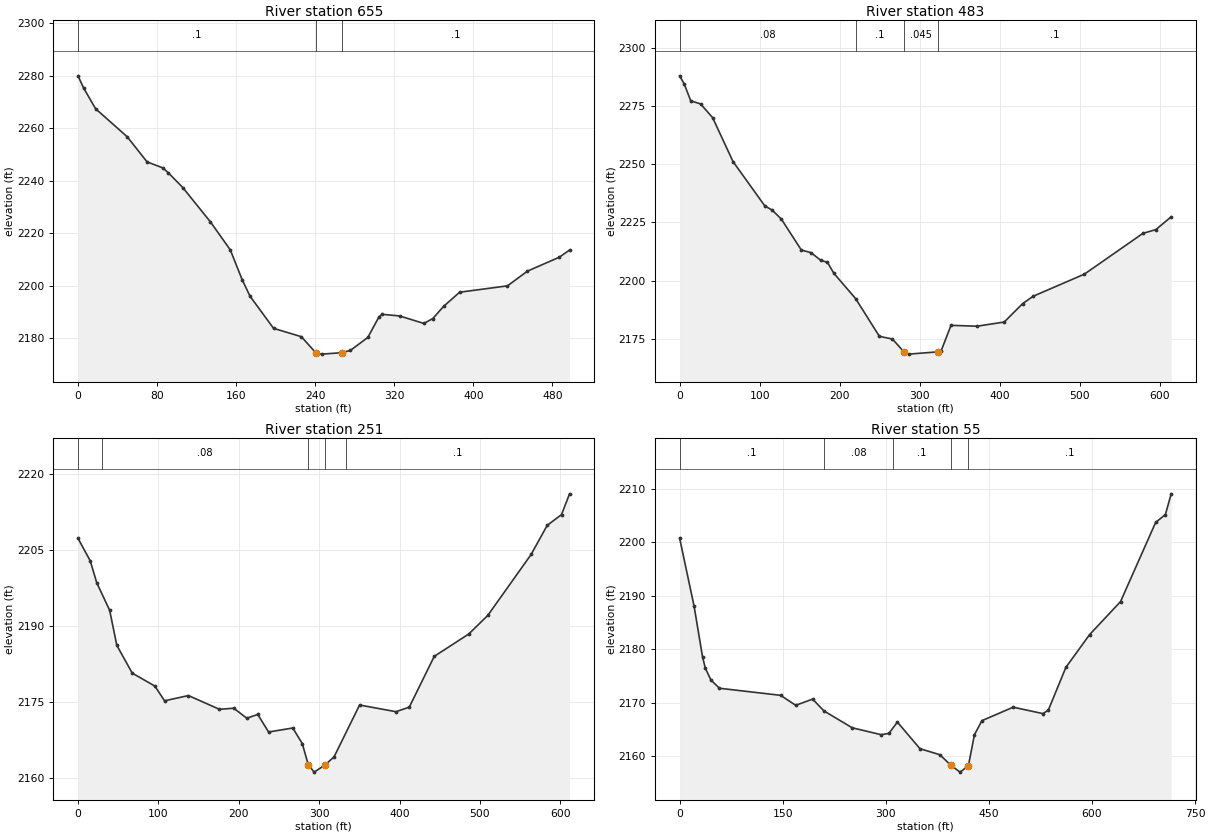
Type RM Length L Ch R = 1 ,655     ,181,172,164.7
XS GIS Cut Line= 4
2251107.98169271664203.4633927812251094.28423928664400.935012975
2251021.23115435664526.4950026942251040.63588004 664679.44989926
#Sta/Elev= 30
       0 2279.91     5.7 2275.27    17.8  2267.4    49.8 2256.73    69.9 2247.18
    85.9 2244.87    91.4 2243.03     106 2237.43     134 2224.37   154.1 2213.71
   166.1 2202.39   174.1 2196.06   197.9 2183.86     226 2180.69   240.6 2174.59
   246.5 2174.05  266.89 2174.59   275.7 2175.47   293.3 2180.41   304.7 2188.32
   307.9 2189.19   325.5 2188.57   349.9 2185.73     359 2187.56   370.1 2192.27
   386.2  2197.6   434.6 2200.02   454.8 2205.62     487 2210.91   497.4 2213.64
#Mann= 3, -1 ,  0
       0     0.1       0   240.6   0.045       0  266.89     0.1       0
Bank Sta=240.6,266.89
XS Rating Curve= 0 ,0
Exp/Cntr(USF)=0,0
Exp/Cntr=0.3,0.1

Type RM Length L Ch R = 1 ,483     ,236,231.7,225.2
XS GIS Cut Line= 2
2250857.84673043664167.5235358482250968.24913945664771.896172345
#Sta/Elev= 30
       0 2288.01     5.7 2284.55    13.9 2277.24    26.1 2275.96    41.2 2270.06
    66.7 2251.18   106.6 2232.05   115.5 2230.35   127.2 2226.42   152.1 2213.16
   164.3 2212.01   176.5  2208.7   184.7 2207.89   192.8 2203.14     220 2192.25
   249.7 2176.05     266 2174.89   280.32169.405   286.3 2168.41   323.32169.404
     327 2169.94   339.2 2180.78   371.7 2180.41   405.7  2182.2   428.6 2190.08
   441.9 2193.29   505.9 2202.78   579.1 2220.31   595.3 2221.94   614.4 2227.42
#Mann= 4, -1 ,  0
       0    0.08       0     220     0.1       0   280.3   0.045       0
   323.3     0.1       0
Bank Sta=280.3,323.3
XS Rating Curve= 0 ,0
Exp/Cntr(USF)=0,0
Exp/Cntr=0.3,0.1

Type RM Length L Ch R = 1 ,251     ,196,196.1,195.1
XS GIS Cut Line= 3
2250636.42219662664266.0140989252250655.25986868664458.852923964
2250851.05959849664827.902715143
#Sta/Elev= 30
       0 2207.39    15.2 2202.95    23.3 2198.62    39.4 2193.16    48.3 2186.24
    67.5 2180.75    95.6  2178.2   107.7 2175.28   137.4 2176.32     176  2173.6
   193.8 2173.82     210 2171.84   223.6 2172.59   237.1 2169.12   267.2 2169.91
     279 2166.84   286.52162.627   293.8 2161.19   307.42162.607   318.6 2164.22
   350.3 2174.45   395.6 2173.13   412.1 2174.03   443.2 2184.07   486.2 2188.49
   509.8 2192.16   563.7  2204.2   583.7 2209.95   601.5 2212.07   611.5 2216.18
#Mann= 5, -1 ,  0
       0     0.1       0      30    0.08       0   286.5   0.045       0
   307.4    0.08       0  333.76     0.1       0
Bank Sta=286.5,307.4
XS Rating Curve= 0 ,0
Exp/Cntr(USF)=0,0
Exp/Cntr=0.3,0.1

Type RM Length L Ch R = 1 ,55      ,,,
XS GIS Cut Line= 4
 2250632.3929663664280.7791807292250543.38370702664658.983234854
2250566.99834524 664696.687266972250783.00673979664878.241552893
#Sta/Elev= 30
       0 2200.74      21 2188.06    33.3 2178.58    37.4 2176.43    45.6 2174.22
    57.9 2172.69   146.9 2171.37   168.9  2169.5   193.5 2170.66     210 2168.45
   251.1  2165.3   293.2 2164.01   304.5 2164.25   316.8 2166.37   349.7 2161.39
   378.5 2160.27  394.97 2158.26   408.1 2157.01   420.2 2158.22   428.9 2163.99
   439.8 2166.63   485.3 2169.15   528.6 2167.95   536.4 2168.59     562  2176.6
   596.5 2182.72   641.5 2188.89   692.6  2203.7   706.8 2205.17   715.2 2209.04
#Mann= 5, -1 ,  0
       0     0.1       0     210    0.08       0     310     0.1       0
  394.97   0.045       0   420.2     0.1       0
Bank Sta=394.97,420.2
XS Rating Curve= 0 ,0
Exp/Cntr(USF)=0,0
Exp/Cntr=0.3,0.1
LCMann Table=0

Chan Stop Cuts=-1
Use User Specified Reach Order=0
Composite Channel Slope=5